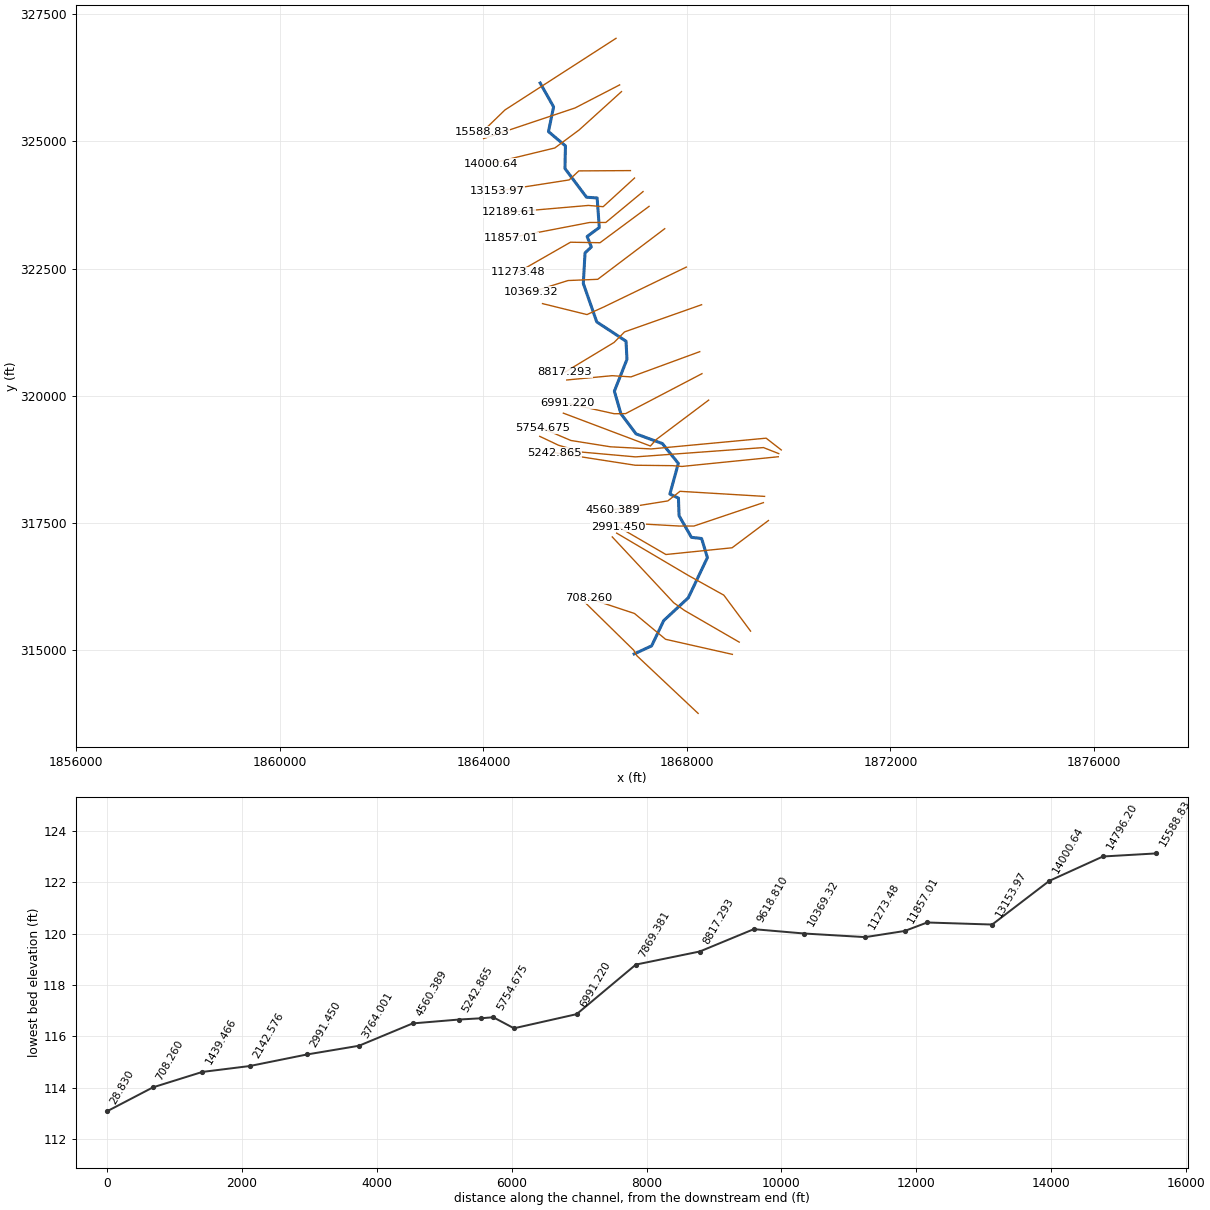
--- LeithCreek.prj (project) ---

Proj Title=Leith Creek Approximate Study
Current Plan=p02
Default Exp/Contr=.3,.1
English Units
Geom File=g02
Geom File=g01
Flow File=f01
Plan File=p02
Plan File=p01
Y Axis Title=Elevation
X Axis Title(PF)=Main Channel Distance
X Axis Title(XS)=Station
BEGIN DESCRIPTION:
Approximate Study of Leith Creek
END DESCRIPTION:

--- LeithCreek.p02 (plan) ---

Plan Title=100 yr Run with Modified Geometry
Version=September 1998 Version 2.2
Short Identifier=Plan02
Geom File=g02
Flow File=f01
Interactive Comp Mode
Subcritical Flow
K Sum by GR= 0
Std Step Tol= 0.01
Critical Tol= 0.01
Num of Std Step Trials= 20
Max Error Tol= 0.3
Flow Tol Ratio= 0.001
Log Output Level= 0
Friction Slope Method= 1
Parabolic Critical Depth
Global Vel Dist= 0 , 0 , 0
Global Log Level= 0
Encroach Param=-1 ,0,0, 2
Encroach River=Leith Creek
Encroach Reach=Leith Creek
Encroach Node=15588.83
       1 1255.42 1982.52
Encroach Node=14796.20
       4      .7
Encroach Node=14000.64
       4      .7
Encroach Node=13153.97
       4      .7
Encroach Node=12189.61
       4      .7
Encroach Node=11857.01
       4      .7
Encroach Node=11273.48
       4      .7
Encroach Node=10369.32
       4      .7
Encroach Node=9618.810
       4      .7
Encroach Node=8817.293
       4      .7
Encroach Node=7869.381
       4      .7
Encroach Node=6991.220
       4      .7
Encroach Node=6062.567
       4      .7
Encroach Node=5754.675
       4      .7
Encroach Node=5653.343
       4      .7
Encroach Node=5574.527
       4      .7
Encroach Node=5242.865
       4      .7
Encroach Node=4560.389
       4      .7
Encroach Node=3764.001
       4      .7
Encroach Node=2991.450
       4      .7
Encroach Node=2142.576
       4      .7
Encroach Node=1439.466
       4      .7
Encroach Node=708.260
       4      .7
Encroach Node=28.830
       4      .7

--- LeithCreek.p01 (plan) ---

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Plan Title=100 yr Flood Event Simulation
Short Identifier=Plan01
Geom File=g01
Flow File=f01

--- LeithCreek.f01 (steady flow) ---

Flow Title=Flow data of Lieth Creek
Version=September 1998 Version 2.2
Number of Profiles= 2
Profile Names=100 yr,Floodway
River Rch & RM=Leith Creek,Leith Creek     ,15588.83
    3660    3660
River Rch & RM=Leith Creek,Leith Creek     ,11857.01
    3710    3710
River Rch & RM=Leith Creek,Leith Creek     ,5242.865
    4030    4030
River Rch & RM=Leith Creek,Leith Creek     ,2142.576
    4114    4114
Boundary for River Rch & Prof#=Leith Creek,Leith Creek     , 1
Up Type= 0
Dn Type= 3
Dn Slope=.001368
Boundary for River Rch & Prof#=Leith Creek,Leith Creek     , 2
Up Type= 0
Dn Type= 3
Dn Slope=.001368
DSS Import GetInterval= 0
DSS Import GetPeak= 0
DSS Import FillOption= 0

--- LeithCreek.g02 (geometry) ---

Geom Title=Modified Geometry of Leith Creek
Version=September 1998 Version 2.2

River Reach=Leith Creek     ,Leith Creek
Reach XY= 30
     1865115.807      326147.825       1865379.9      325680.101
     1865278.944       325193.44       1865612.6      324912.401
     1865603.387        324467.4       1866026.5      323903.401
     1866235.501      323890.001       1866277.9      323308.301
       1866039.1      323132.501       1866120.9      322925.901
       1865997.4      322808.901       1865963.9      322207.801
     1866227.901      321453.301     1866803.601      321074.001
       1866821.5      320717.401     1866574.301      320092.001
     1866702.396      319648.521       1867000.4      319252.501
     1867517.101      319062.301        1867831.      318673.001
       1867665.1      318069.001       1867833.6      317991.101
     1867845.301      317645.001       1868088.9      317218.801
       1868288.4      317196.501     1868402.501      316821.601
     1868027.401      316031.601       1867543.9      315583.101
       1867306.3      315086.001     1866963.646      314927.813

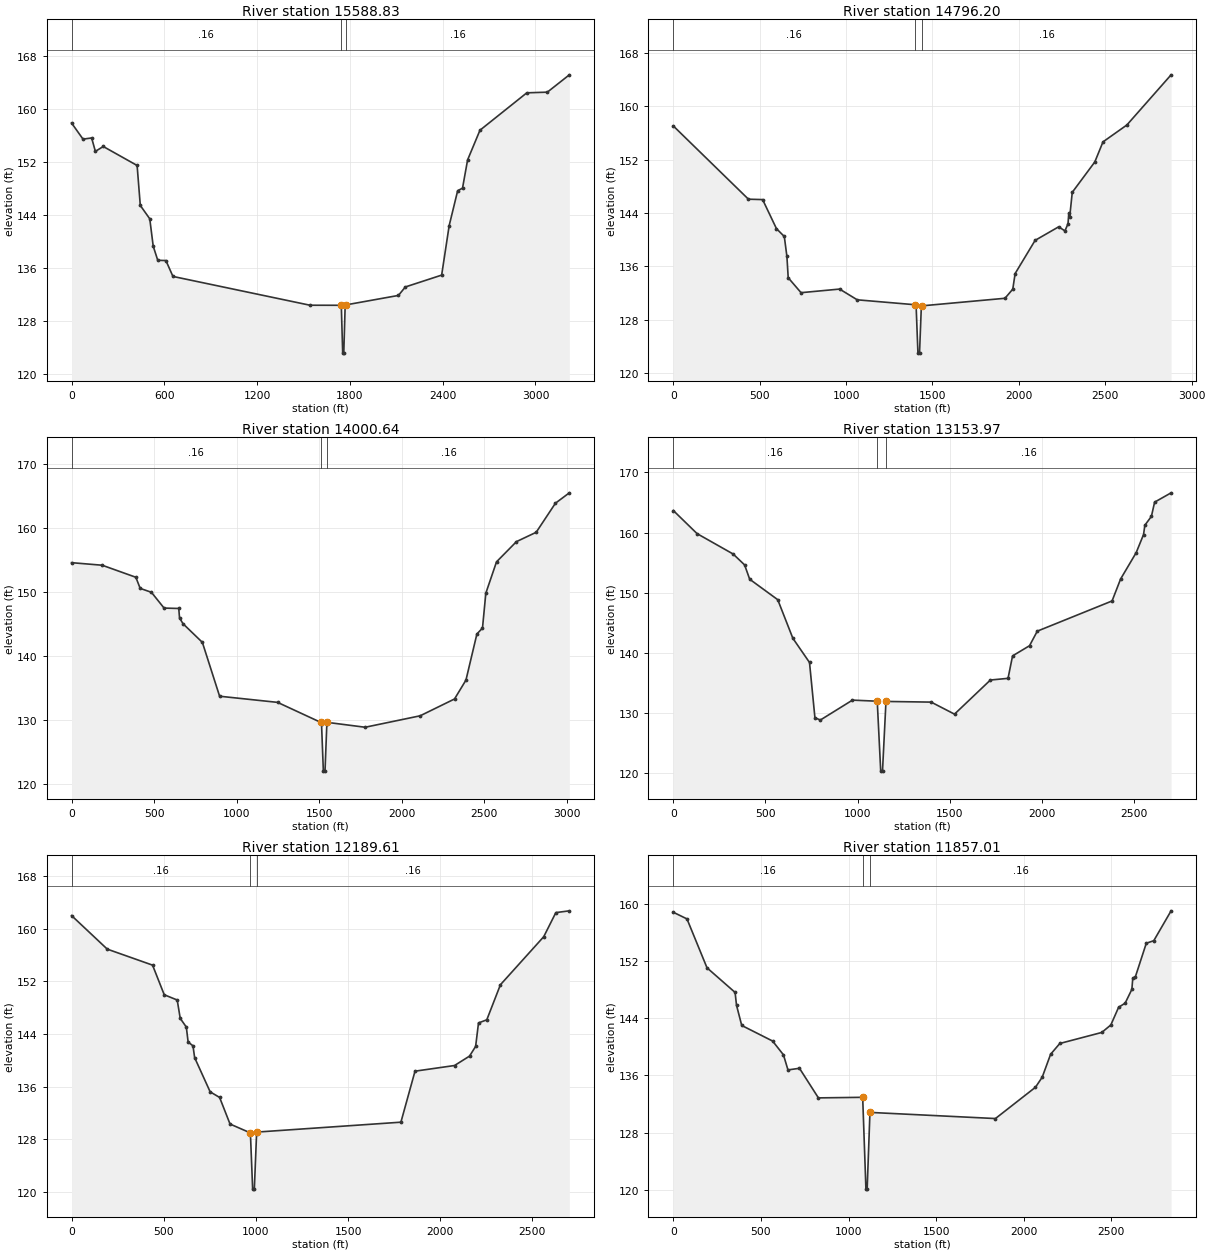
Type RM Length L Ch R = 1 ,15588.83,715,792.32,553.03
XS GIS Cut Line= 3
     1866606.414       327026.48     1864424.598      325619.601
     1863977.164      325186.005
#Sta/Elev= 30
       0   157.9   74.11  155.46   129.9  155.64  154.05  153.61  205.05  154.35
  423.99  151.48   444.5  145.44  505.73  143.42  528.03  139.29  557.46  137.15
  610.19  137.11  655.74  134.71 1541.73  130.36 1739.62  130.35 1744.46  130.29
 1753.42  123.12 1760.42  123.12 1769.43  130.33 1774.21  130.41 2113.86  131.84
 2158.59  133.12 2393.36  134.91 2442.09   142.4 2496.94  147.67 2528.28  148.05
 2561.15  152.32 2641.22  156.81 2944.03  162.46 3076.84  162.56 3219.14  165.18
#Mann= 3 , 0 , 0
       0     .16       0 1739.62     .07       0 1774.21     .16       0
Bank Sta=1739.62,1774.21
Exp/Cntr=.3,.1

Type RM Length L Ch R = 1 ,14796.20,443.47,795.56,623.82
XS GIS Cut Line= 3
     1866677.709      326111.306     1865800.847      325657.725
     1864004.959      325056.851
#Sta/Elev= 30
       0  157.05  434.85  146.07  516.97  146.01  597.13  141.65  642.45  140.48
  657.48  137.49  664.98   134.3  739.27  132.06  962.56   132.6 1064.51  130.99
 1400.24  130.25  1405.2  130.13 1415.86     123 1425.01     123 1435.55  130.02
 1440.69  130.09 1919.57  131.22 1964.71  132.59 1978.37  134.93 2093.98   139.9
 2230.21  141.93 2266.59  141.32 2284.49   142.4 2288.66  143.93 2294.39  143.46
 2308.97   147.1  2439.4  151.65 2486.79  154.66 2624.96  157.19 2880.97  164.71
#Mann= 3 , 0 , 0
       0     .16       0 1400.24     .07       0 1440.69     .16       0
Bank Sta=1400.24,1440.69
Exp/Cntr=.3,.1

Type RM Length L Ch R = 1 ,14000.64,879.26,846.67,663.86
XS GIS Cut Line= 4
     1866714.322      325979.499     1865882.693      325226.776
     1865404.294      324871.835     1864144.088      324566.237
#Sta/Elev= 30
       0  154.64   185.6  154.24  389.24  152.36  415.56  150.62  483.44  150.01
  560.26  147.54  649.11  147.48  653.83     146  675.16  145.09  792.06  142.18
  896.46  133.76  1247.4   132.8 1510.07  129.66 1513.55  129.47 1524.68  122.05
 1534.68  122.05  1545.8  129.46 1549.29  129.67 1777.69  128.91 2110.81   130.7
 2318.87  133.33  2388.1  136.28 2454.36  143.49 2488.25  144.42 2508.46  149.87
 2573.18  154.77 2693.81  157.93 2813.37  159.39 2930.02  163.94 3014.12  165.56
#Mann= 3 , 0 , 0
       0     .16       0 1510.07     .07       0 1549.29     .16       0
Bank Sta=1510.07,1549.29
Exp/Cntr=.3,.1

Type RM Length L Ch R = 1 ,13153.97,622.62,964.36,576.5
XS GIS Cut Line= 4
     1866890.065      324427.107     1865875.713      324421.187
     1865686.283      324243.802     1864275.895      324024.364
#Sta/Elev= 30
       0  163.66  128.94  159.82  324.75  156.43  386.92  154.62   414.5  152.24
  566.71  148.84   648.7  142.43  739.07  138.41  768.49  129.23  797.88  128.84
  972.13  132.15 1106.66  131.97 1125.52  120.35  1135.2  120.35 1154.02  131.93
 1399.32  131.82 1525.89  129.82 1720.65  135.49 1816.39  135.77 1840.97   139.5
 1932.97  141.19 1975.13  143.61 2380.92  148.63 2427.29  152.28 2511.84  156.66
  2551.8  159.67 2558.81  161.21 2594.46  162.69 2611.79  165.05 2701.24   166.6
#Mann= 3 , 0 , 0
       0     .16       0 1106.66     .07       0 1154.02     .16       0
Bank Sta=1106.66,1154.02
Exp/Cntr=.3,.1

Type RM Length L Ch R = 1 ,12189.61,296.83,332.6,379.04
XS GIS Cut Line= 4
     1866970.613      324280.655     1866354.222      323717.604
     1866064.187      323742.499     1864495.573      323606.975
#Sta/Elev= 30
       0  161.99  193.74  156.89  439.41  154.46  502.77  149.96  573.16  149.16
  589.56  146.37   622.6  145.05  632.39  142.78  658.73   142.2  667.67  140.41
  751.91  135.21  803.14  134.36  859.73  130.32  966.98  129.01  970.47  128.78
  982.39  120.43  991.53  120.43 1003.67  128.81 1007.12   129.1 1786.65   130.6
 1863.18  138.35 2077.62  139.21 2158.99  140.64 2192.01  142.11 2207.63  145.68
 2252.51  146.15 2326.49  151.48 2561.47  158.78 2627.14  162.44  2700.4  162.71
#Mann= 3 , 0 , 0
       0     .16       0  966.98     .07       0 1007.12     .16       0
Bank Sta=966.98,1007.12
Exp/Cntr=.3,.1

Type RM Length L Ch R = 1 ,11857.01,287.36,583.53,338.09
XS GIS Cut Line= 4
     1867138.259      324014.685     1866405.581       323407.42
     1866088.747       323407.42     1864544.181      323110.388
#Sta/Elev= 30
       0  158.82   78.02  157.89  192.39  151.05  352.64  147.61  360.83  145.81
  390.53  142.99  566.76  140.81   628.7  138.88  654.48  136.77  720.15     137
  828.21  132.86 1080.93  132.94 1099.48   120.1 1106.47   120.1 1122.41  130.83
 1838.67  129.97 2067.35  134.35  2105.8  135.76 2153.58  138.96 2206.16  140.47
 2445.62  142.01  2497.4  143.06 2541.72  145.53 2579.07  146.11 2617.44  148.04
 2622.58   149.6 2637.21  149.78 2699.82  154.49 2742.41  154.84 2841.32  159.02
#Mann= 3 , 0 , 0
       0     .16       0 1080.93     .07       0 1122.41     .16       0
Bank Sta=1080.93,1122.41
Exp/Cntr=.3,.1

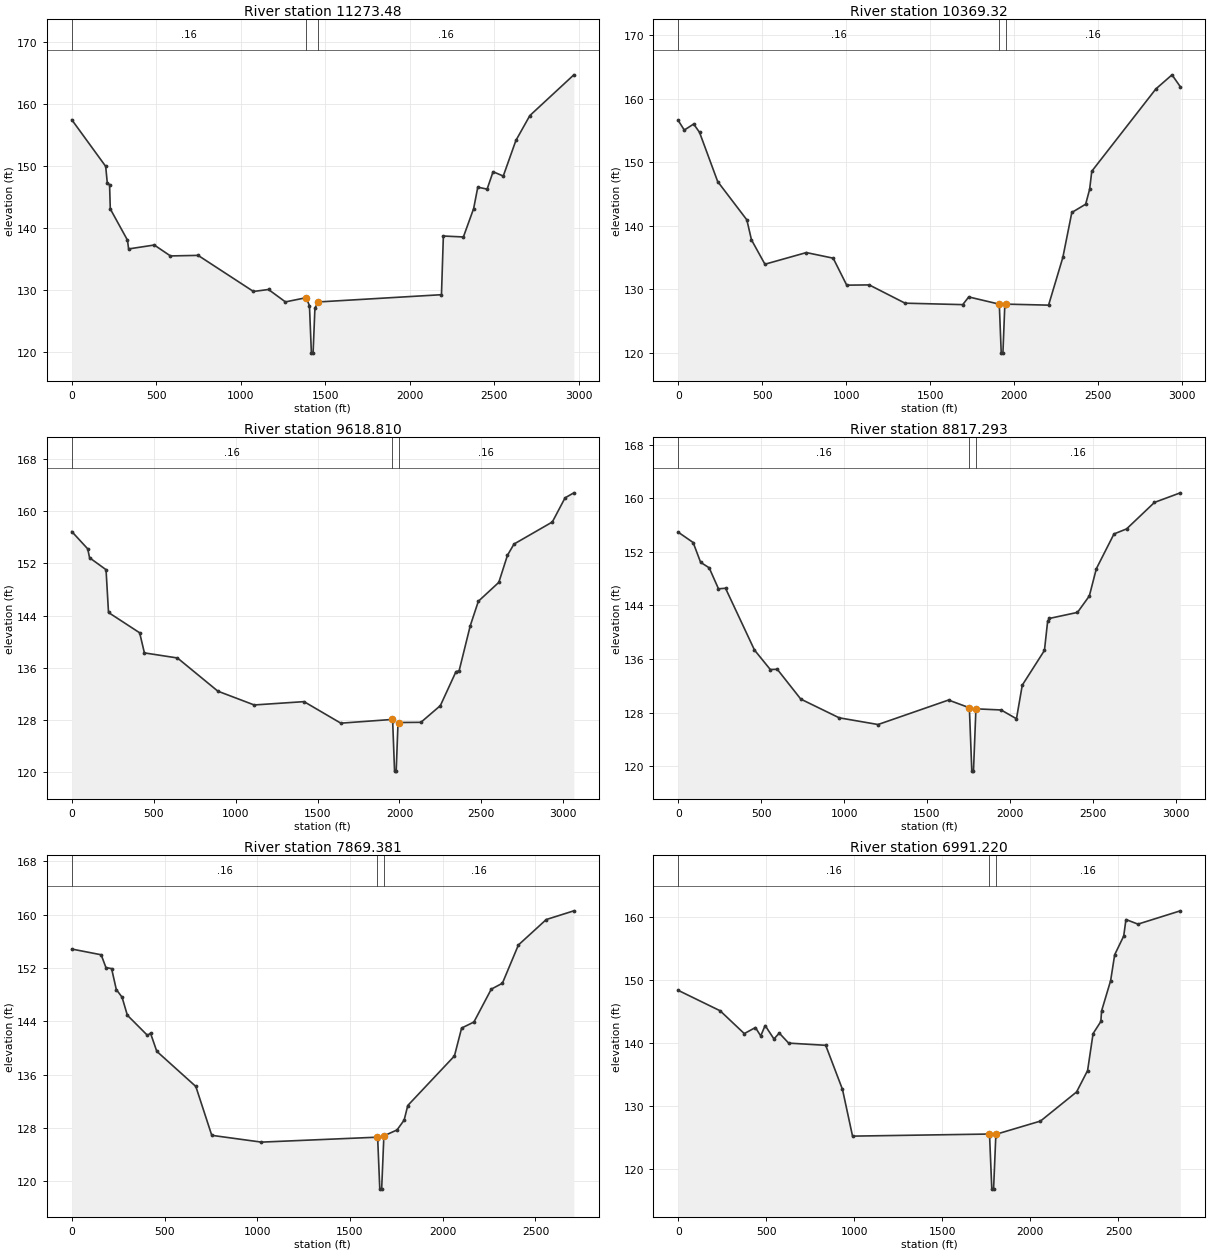
Type RM Length L Ch R = 1 ,11273.48,631.55,904.16,759.35
XS GIS Cut Line= 4
     1867256.195      323724.137     1866292.219      323009.728
     1865712.274      323019.468     1864678.638      322428.036
#Sta/Elev= 30
       0  157.49  200.75  149.97  210.11  147.29  223.66  147.02  227.95  143.11
  329.52  138.08  336.32  136.66  488.05  137.29  583.98  135.53  747.44  135.62
 1075.11   129.8 1164.05  130.12 1264.15  128.12 1387.32   128.8 1406.38   127.5
 1417.85  119.86 1427.85  119.86 1438.76  127.13 1458.39  128.11 2187.48  129.28
 2198.68  138.74 2317.21  138.59 2377.92  143.17 2402.42  146.62 2457.61   146.3
  2492.8  149.11 2553.12  148.41 2627.91  154.15 2710.42  158.16 2970.75  164.73
#Mann= 3 , 0 , 0
       0     .16       0 1387.32     .07       0 1458.39     .16       0
Bank Sta=1387.32,1458.39
Exp/Cntr=.3,.1

Type RM Length L Ch R = 1 ,10369.32,683.71,750.51,603.24
XS GIS Cut Line= 4
     1867563.744      323284.781     1866247.279      322290.331
      1865664.33      322266.496     1864942.252      322039.938
#Sta/Elev= 30
       0  156.56   36.03  155.05    91.9     156  126.82  154.69  234.89  146.96
   408.6  140.94  436.13   137.8   516.3  133.97  763.04   135.8  922.82  134.92
 1003.33  130.68  1137.4  130.72 1350.78  127.85 1694.26  127.62 1730.18  128.83
 1907.67  127.72  1912.4  127.47  1923.6     120  1933.6     120  1944.7   127.4
 1949.53   127.7 2205.53  127.54 2290.45  135.03 2343.95   142.1 2426.32   143.4
 2450.15  145.75 2462.82  148.58 2844.34  161.51 2940.66  163.73 2990.07  161.86
#Mann= 3 , 0 , 0
       0     .16       0 1907.67     .07       0 1949.53     .16       0
Bank Sta=1907.67,1949.53
Exp/Cntr=.3,.1

Type RM Length L Ch R = 1 ,9618.810,674.26,801.52,970.82
XS GIS Cut Line= 4
     1867988.455      322530.553     1866376.669      321751.916
     1866035.761      321597.327      1865161.93      321812.937
#Sta/Elev= 30
       0  156.89   97.44  154.23  108.62  152.87  209.15  151.04  224.25  144.48
  414.31  141.37  443.29  138.29  645.05  137.51  891.92  132.42 1113.47  130.31
 1417.52  130.82 1642.12  127.52 1955.32  128.09 1958.55  127.86 1970.08  120.17
 1980.08  120.17 1990.98  127.44 1994.84  127.62 2131.03  127.65 2249.66  130.21
 2345.05  135.42 2364.12  135.55 2432.12  142.45 2481.51   146.2 2606.43   149.1
 2659.23  153.25 2699.17  154.97 2932.98  158.35 3010.72  162.05 3064.37  162.82
#Mann= 3 , 0 , 0
       0     .16       0 1955.32     .07       0 1994.84     .16       0
Bank Sta=1955.32,1994.84
Exp/Cntr=.3,.1

Type RM Length L Ch R = 1 ,8817.293,888.25,947.91,433.76
XS GIS Cut Line= 4
     1868288.682       321790.97     1866774.554      321256.994
     1866567.559      321048.802     1865601.286      320465.578
#Sta/Elev= 30
       0  154.93   89.95  153.39  134.88  150.44  186.59  149.62  242.65  146.49
   285.2  146.57  459.71  137.36  555.22  134.45  597.25  134.49  739.05  130.04
  970.71  127.25 1205.03  126.25 1630.02   129.9 1755.67  128.75 1770.45   119.3
 1780.45   119.3 1795.22  128.59  1947.1  128.42 2039.71  127.11 2074.69  132.12
  2208.4   137.3 2227.68  141.65 2238.27  142.07 2407.73  142.97 2479.11  145.42
  2521.3  149.48 2627.83  154.67 2703.82  155.42 2871.84  159.37 3027.75   160.8
#Mann= 3 , 0 , 0
       0     .16       0 1755.67     .07       0 1795.22     .16       0
Bank Sta=1755.67,1795.22
Exp/Cntr=.3,.1

Type RM Length L Ch R = 1 ,7869.381,551.13,878.16,669.55
XS GIS Cut Line= 4
     1868252.069      320868.321     1866901.048      320372.825
     1866529.223       320396.42     1865637.899      320311.804
#Sta/Elev= 30
       0  154.85  158.51  153.99   184.2  152.07  214.76  151.91   240.1  148.77
  271.05  147.62  299.68  144.91  408.21  141.88  424.56  142.21  458.31  139.49
  668.87  134.21  754.76  126.87 1022.44  125.85 1645.72  126.59  1649.4  126.35
 1660.74  118.79 1670.74  118.79 1682.42  126.58 1685.76  126.83 1753.69  127.68
 1791.98  129.16 1811.59  131.35 2063.12  138.79 2101.81  142.98 2168.11  143.89
 2261.83  148.83 2321.65  149.71 2408.02  155.46 2558.08  159.28 2706.92  160.59
#Mann= 3 , 0 , 0
       0     .16       0 1645.72     .07       0 1685.76     .16       0
Bank Sta=1645.72,1685.76
Exp/Cntr=.3,.1

Type RM Length L Ch R = 1 ,6991.220,682.73,928.65,377.57
XS GIS Cut Line= 4
     1868296.005      320436.288     1866794.973      319650.956
     1866571.429      319648.543     1865659.867      319850.479
#Sta/Elev= 30
       0   148.4  237.93  145.16  375.08  141.54   438.4   142.5  468.45  141.17
  493.47  142.82  543.55  140.69  573.89  141.62  627.04  140.03  837.47  139.68
  932.82  132.68  989.88  125.27 1764.85   125.6 1768.28  125.22 1780.82  116.86
 1790.82  116.86 1803.38  125.23 1806.79  125.58 2057.28  127.66 2262.23  132.28
 2324.76  135.68 2355.92  141.54 2400.05  143.46 2404.05  145.12 2455.64  149.95
 2478.52  154.05 2529.84  157.02 2542.61  159.64 2610.86  158.91 2851.28  161.02
#Mann= 3 , 0 , 0
       0     .16       0 1764.85     .07       0 1806.79     .16       0
Bank Sta=1764.85,1806.79
Exp/Cntr=.3,.1

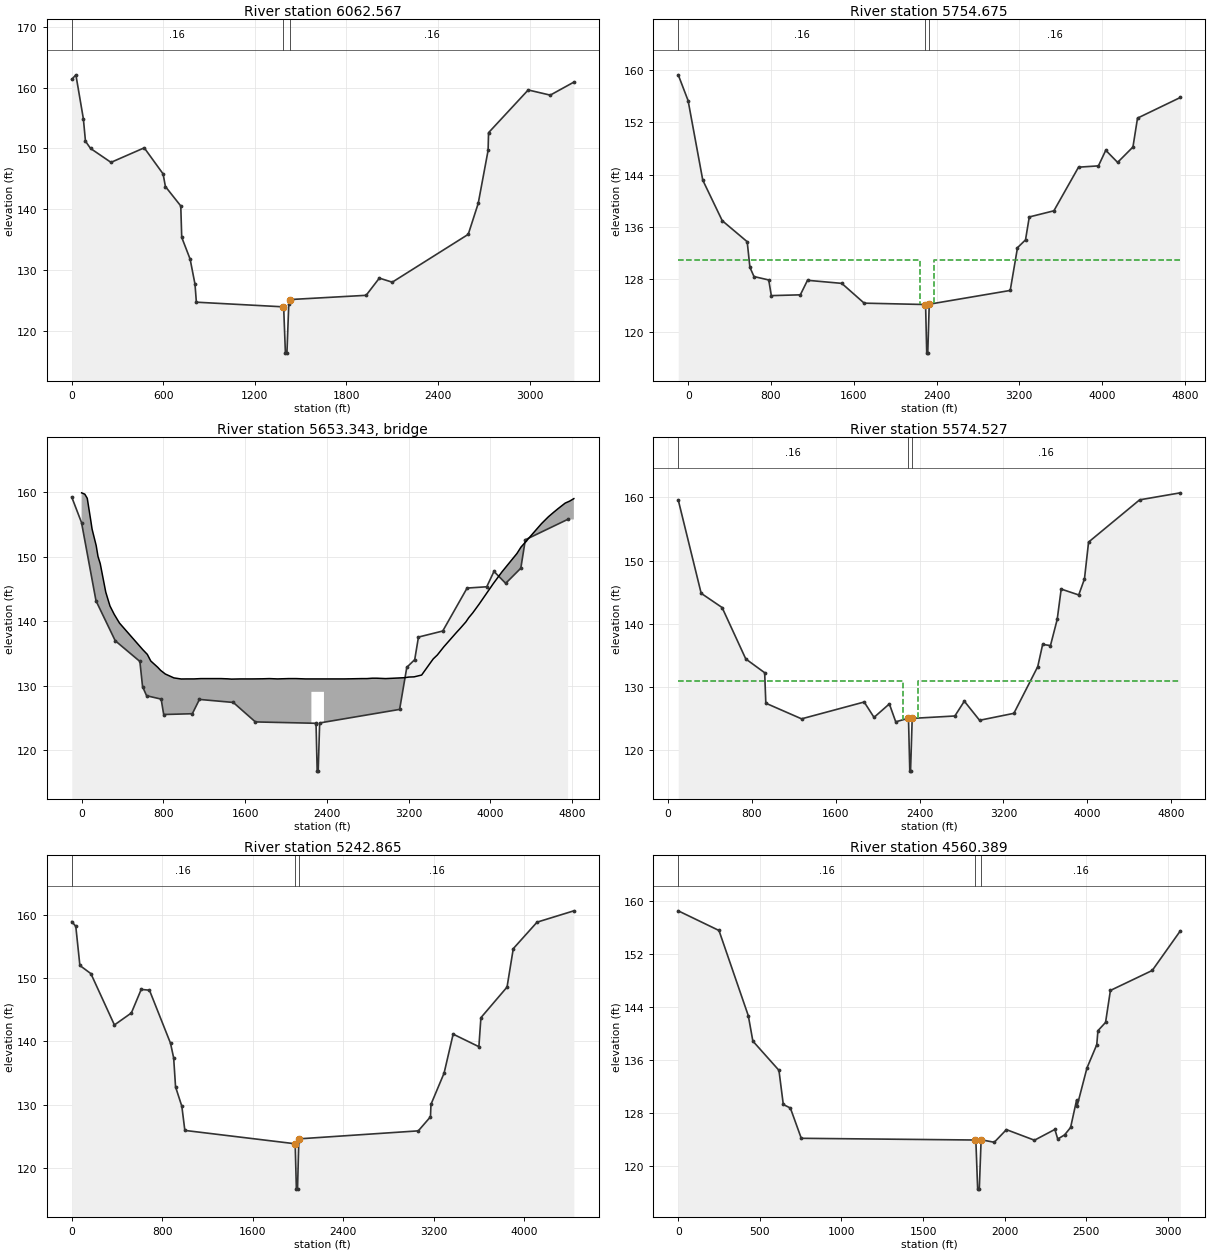
Type RM Length L Ch R = 1 ,6062.567,396.74,307.89,441.67
XS GIS Cut Line= 4
     1868427.811      319916.383     1867391.878      319137.937
      1867283.14      319013.884     1865571.996      319660.092
#Sta/Elev= 30
       0  161.34   26.97  162.09      76  154.86   89.77  151.17  123.08  149.98
  256.97  147.69   474.9  150.08  598.38  145.79  613.63  143.71  714.25  140.52
  720.46  135.36  775.55  131.77  807.48  127.65  816.41  124.69  1381.9  123.93
 1388.84  123.65 1399.85  116.31 1409.85  116.31 1421.96  124.38 1427.81  125.12
 1928.71  125.82 2015.37  128.65 2100.01  127.98 2597.93  135.85 2663.25  140.94
 2728.03  149.66 2730.94  152.57 2990.79   159.6  3135.4  158.75 3289.88  160.89
#Mann= 3 , 0 , 0
       0     .16       0  1381.9     .07       0 1427.81     .16       0
Bank Sta=1381.9,1427.81
Exp/Cntr=.5,.3

Type RM Length L Ch R = 1 ,5754.675,164.4,180.15,276.86
XS GIS Cut Line= 6
     1869854.255      318936.705     1869556.526      319168.271
     1867296.514      318956.638     1866497.618      318998.802
     1865718.694      319123.075     1865157.247      319362.743
#Sta/Elev= 30
   -96.4  159.23   -1.05  155.29  140.74  143.15  328.87  136.96  570.12  133.75
  596.31  129.84  635.85  128.43  778.19  127.91  803.22  125.52 1083.66  125.64
 1152.96  127.86 1484.24  127.39 1700.62  124.37 2290.93  124.16 2294.38     124
 2305.27  116.74 2315.27  116.74  2329.6  124.21 3112.18  126.31 3182.52  132.84
 3259.97  134.03 3296.51  137.53 3534.19  138.47 3772.38  145.13 3964.83  145.33
 4035.52  147.71 4150.23  145.86 4298.36  148.21 4342.53  152.62 4756.12  155.77
#Mann= 3 , 0 , 0
   -96.4     .16       0 2290.93     .07       0  2329.6     .16       0
#XS Ineff= 2 , 0
   -96.4  2242.6     131  2376.6   -96.4     131
Bank Sta=2290.93,2329.6
Exp/Cntr=.5,.3

Type RM Length L Ch R = 3 ,5653.343,,,
BEGIN DESCRIPTION:
NC 83 Across Leith Creek - Data Available from NCDOT Bridge Inspection Reports
END DESCRIPTION:
Bridge Culvert--1,0,-1,-1, 0
Deck Dist Width WeirC Skew NumUp NumDn MinLoCord MaxHiCord MaxSubmerge Is_Ogee
81.33,40,2.6,,74,74,131.04,,.95,0,2,2,,
       0   31.23   55.17   91.01  102.39  142.55  160.31  182.03  236.42  277.31
  318.54  370.14  554.25  598.57  642.78  676.91  744.35     773  819.11  902.89
  974.24 1029.58 1100.02  1166.1 1251.42 1365.19 1432.19 1467.18  1552.9 1672.35
 1773.13 1837.32 1916.95 2025.03 2098.98 2189.99 2248.76 2363.27 2371.76 2480.09
  2571.1 2741.75 2792.95 2844.14 2889.65 2974.97 3054.61 3159.83 3203.28  3253.7
 3327.65 3412.45 3441.41 3481.23  3543.8  3669.2 3703.07 3761.08  3788.4 3828.21
 3890.78 4026.64 4112.63  4260.2 4300.34 4340.16 4408.42 4501.13 4567.69 4617.85
 4662.37 4732.65 4775.61 4817.26
   159.9  159.69  159.05  155.47  154.27  151.72  150.03  148.93  144.49  142.36
  141.07  139.71  136.38  135.58  134.85  133.82  132.85  132.37   131.8   131.2
  131.03  131.04  131.04  131.09  131.09  131.09  131.05  131.01  131.04  131.04
  131.06  131.09  131.04  131.09  131.09  131.04  131.04  131.04  131.04  131.04
  131.04  131.09  131.09  131.15  131.15  131.09  131.15  131.23  131.33  131.36
  131.64  133.52  134.15  134.75     136  138.26  138.84  139.89  140.53  141.29
  142.65  145.77  147.62  150.49  151.49   152.2  153.45  155.13  156.18  156.86
  157.44  158.31  158.61     159
                                                                                
                                                                                
                                                                                
                                                  129.04  129.04  129.04
                                                                                
                                                                                
                                                                                
                                
       0   31.23   55.17   91.01  102.39  142.55  160.31  182.03  236.42  277.31
  318.54  370.14  554.25  598.57  642.78  676.91  744.35     773  819.11  902.89
  974.24 1029.58 1100.02  1166.1 1251.42 1365.19 1432.19 1467.18  1552.9 1672.35
 1773.13 1837.32 1916.95 2025.03 2098.98 2189.99 2248.76 2363.27 2371.76 2480.09
  2571.1 2741.75 2792.95 2844.14 2889.65 2974.97 3054.61 3159.83 3203.28  3253.7
 3327.65 3412.45 3441.41 3481.23  3543.8  3669.2 3703.07 3761.08  3788.4 3828.21
 3890.78 4026.64 4112.63  4260.2 4300.34 4340.16 4408.42 4501.13 4567.69 4617.85
 4662.37 4732.65 4775.61 4817.26
   159.9  159.69  159.05  155.47  154.27  151.72  150.03  148.93  144.49  142.36
  141.07  139.71  136.38  135.58  134.85  133.82  132.85  132.37   131.8   131.2
  131.03  131.04  131.04  131.09  131.09  131.09  131.05  131.01  131.04  131.04
  131.06  131.09  131.04  131.09  131.09  131.04  131.04  131.04  131.04  131.04
  131.04  131.09  131.09  131.15  131.15  131.09  131.15  131.23  131.33  131.36
  131.64  133.52  134.15  134.75     136  138.26  138.84  139.89  140.53  141.29
  142.65  145.77  147.62  150.49  151.49   152.2  153.45  155.13  156.18  156.86
  157.44  158.31  158.61     159
                                                                                
                                                                                
                                                                                
                                                  129.04  129.04  129.04
                                                                                
                                                                                
                                                                                
                                
BR Coef=-1 , 1 , 0 ,, 0 ,,,.8,0,1.2,0,
WSPro=,,,, 1 ,,,, 0 ,,,, 0 ,,,,-1 ,-1 ,-1 , 0 , 0 , 0 , 0 , 0
BC Design=,, 0 ,, 0 ,,,,,,

Type RM Length L Ch R = 1 ,5574.527,280.89,331.66,243.62
XS GIS Cut Line= 6
     1869804.633      318865.029     1869504.148      318983.569
     1866990.847      318800.496     1865945.624        318893.7
     1865477.382      319029.069     1865106.783      319204.382
#Sta/Elev= 30
    96.4  159.59   315.3  144.82   515.1  142.57  741.04  134.44  921.34  132.26
  932.36  127.44 1273.56  124.97 1871.08  127.63 1965.08   125.2 2111.36  127.33
  2172.1   124.5 2291.09  125.05 2294.14  124.91 2306.43   116.7 2313.65   116.7
 2329.43  125.04 2736.54  125.42 2826.94  127.76 2972.33  124.74 3299.82  125.84
 3527.75  133.23 3574.37  136.73 3649.07  136.56 3713.28  140.69 3751.47  145.49
 3918.72  144.56 3973.53  147.09 4012.73  152.92    4500   159.6 4888.31  160.71
#Mann= 3 , 0 , 0
    96.4     .16       0 2291.09     .07       0 2329.43     .16       0
#XS Ineff= 2 , 0
       0  2237.4     131  2389.4       0     131
Bank Sta=2291.09,2329.43
Exp/Cntr=.5,.3

Type RM Length L Ch R = 1 ,5242.865,656.69,682.48,813.77
XS GIS Cut Line= 5
     1869795.674      318803.347     1867901.876      318612.624
     1867718.093       318627.94     1866984.262      318636.259
     1865388.931      318883.896
#Sta/Elev= 30
       0  158.89   35.54  158.14   71.75  151.96  169.04  150.67  376.75  142.57
  526.37  144.46   613.5  148.18  686.37  148.06  872.54  139.68  900.25  137.37
  917.03  132.79  972.55  129.73  999.09  125.92 1969.65  123.82 1974.04  123.69
  1984.6  116.65  1994.6  116.65 2006.08   124.3 2009.56  124.59 3061.77  125.85
 3169.44  128.07 3173.66  130.03 3289.67  134.97 3369.67  141.12 3597.08  139.14
 3615.03  143.72 3845.87  148.55 3901.03  154.62 4111.01   158.8 4436.11  160.59
#Mann= 3 , 0 , 0
       0     .16       0 1969.65     .07       0 2009.56     .16       0
Bank Sta=1969.65,2009.56
Exp/Cntr=.3,.1

Type RM Length L Ch R = 1 ,4560.389,516.38,796.39,455.68
XS GIS Cut Line= 4
     1869526.202      318024.222     1867863.564      318123.781
      1867625.22      317935.212     1866532.721      317760.608
#Sta/Elev= 30
       0  158.55  249.59  155.58  429.27   142.7  457.16  138.87  616.97  134.45
  643.62  129.29  687.07  128.75  753.83  124.18 1820.93  123.92 1823.44   123.8
 1834.39   116.5 1844.39   116.5 1855.36  123.81 1857.84  123.95 1936.08  123.58
 2010.54  125.49 2182.36  123.89  2307.4  125.52 2325.05  124.07 2367.24   124.7
  2403.8  125.82 2440.64  129.97 2443.53  129.06 2503.96   134.8 2564.06  138.32
 2571.22  140.44 2617.94  141.69 2647.64  146.52 2903.96  149.54  3075.9  155.52
#Mann= 3 , 0 , 0
       0     .16       0 1820.93     .07       0 1857.84     .16       0
Bank Sta=1820.93,1857.84
Exp/Cntr=.3,.1

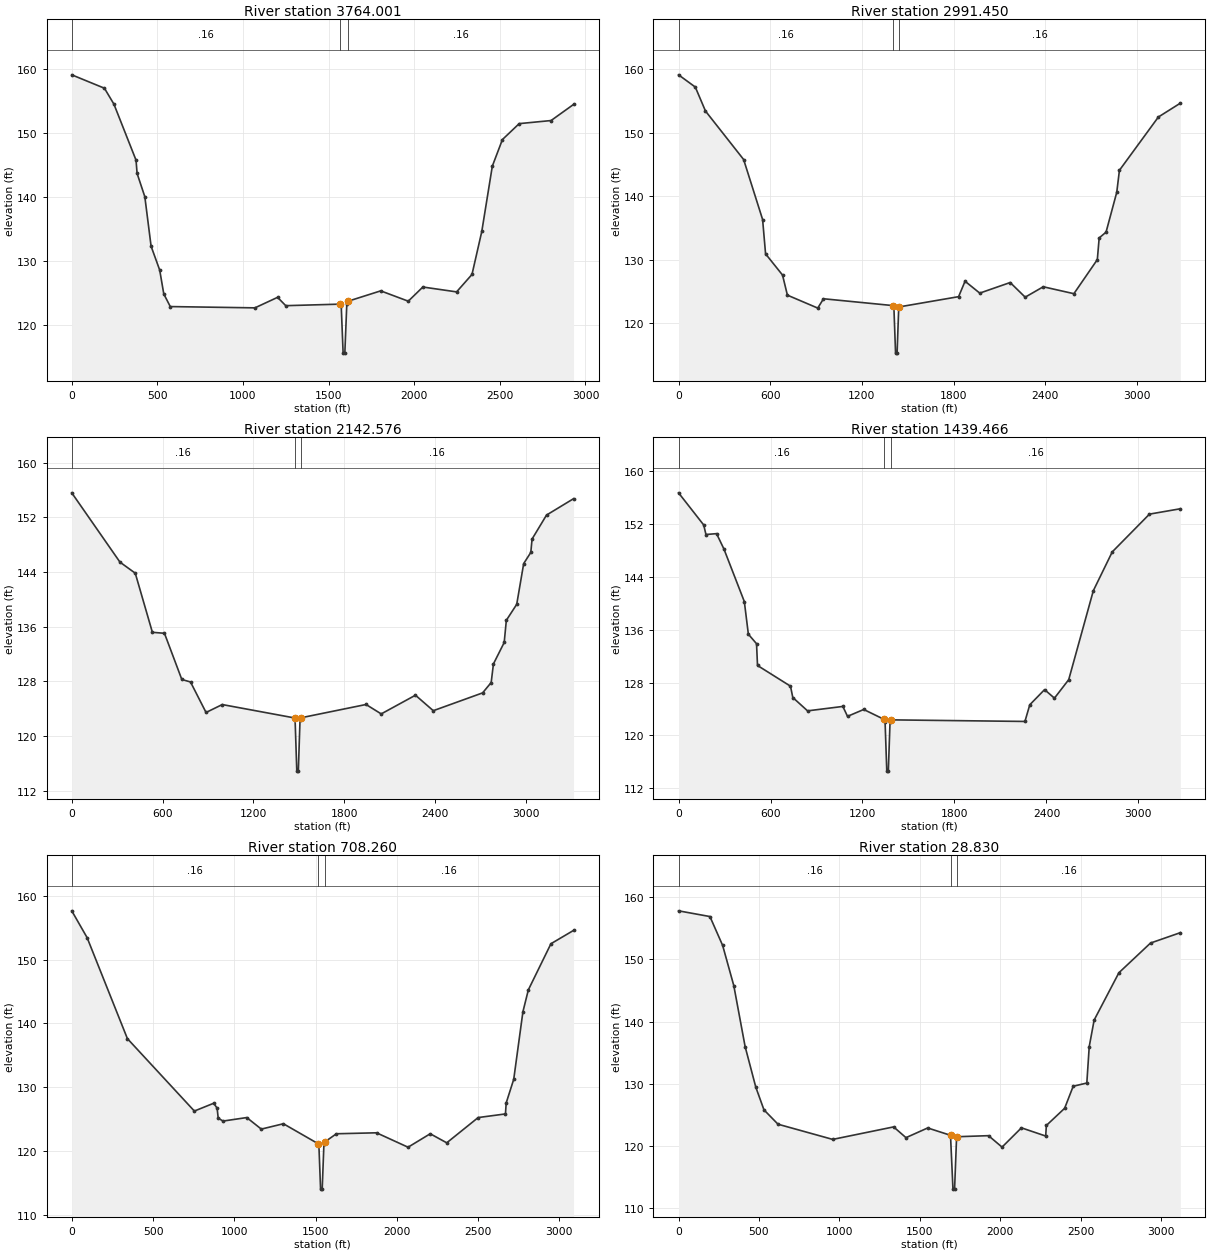
Type RM Length L Ch R = 1 ,3764.001,641.77,772.55,590.33
XS GIS Cut Line= 4
      1869502.77      317901.202     1868137.431      317441.249
     1867849.326      317441.343     1866649.883      317508.711
#Sta/Elev= 30
       0  159.03  190.83  156.94   246.2  154.46  375.39  145.72  381.49  143.66
  426.68  140.02  463.31   132.3  513.54  128.58  537.43  124.86   575.3  122.89
 1069.62  122.69 1201.87  124.33 1249.69  123.03 1567.64  123.27 1573.62  122.99
 1584.66  115.63 1594.66  115.63 1606.12  123.27 1611.67  123.71  1804.1  125.34
 1965.11  123.73 2050.35  125.94 2247.32  125.18 2337.22   127.9 2394.37   134.6
 2455.97  144.79 2515.02  148.94 2612.92  151.42 2798.97   151.9 2930.17  154.41
#Mann= 3 , 0 , 0
       0     .16       0 1567.64     .07       0 1611.67     .16       0
Bank Sta=1567.64,1611.67
Exp/Cntr=.3,.1

Type RM Length L Ch R = 1 ,2991.450,942.57,848.87,152.69
XS GIS Cut Line= 4
     1869602.357      317549.717     1868887.353      317013.907
     1867587.176      316881.896     1866649.883      317426.698
#Sta/Elev= 30
       0  159.16   109.7  157.23  176.31  153.45  425.95  145.81  550.25  136.35
  569.61  130.94  680.58   127.6  712.48  124.43  911.28  122.39  948.79  123.86
 1405.76  122.78 1409.52  122.59 1420.47  115.29 1430.47  115.29 1441.17  122.42
 1445.17  122.58 1833.13  124.19 1875.36  126.62  1971.6  124.75 2170.82  126.42
 2268.98  124.11 2387.25  125.75  2587.8  124.66 2741.19  130.03 2753.29  133.45
 2798.26  134.36 2868.42  140.65 2885.83  144.11  3140.8  152.51 3284.48  154.69
#Mann= 3 , 0 , 0
       0     .16       0 1405.76     .07       0 1445.17     .16       0
Bank Sta=1405.76,1445.17
Exp/Cntr=.3,.1

Type RM Length L Ch R = 1 ,2142.576,651.99,703.11,464.73
XS GIS Cut Line= 4
     1869250.872      315376.368     1868725.566      316082.797
     1868031.217      316468.546     1866619.128      317302.213
#Sta/Elev= 30
       0   155.6  318.46  145.45  419.46  143.83  532.65  135.17  612.35  135.03
  727.05  128.26  784.36   127.9  887.04  123.43  994.09  124.59 1471.69  122.63
 1475.19  122.42 1486.55  114.84 1496.55  114.84 1507.88  122.39 1511.42  122.64
 1943.87   124.6 2044.17  123.22 2270.35  125.96 2388.08  123.69 2713.99   126.3
 2770.52  127.82 2785.35  130.54 2856.47  133.68 2870.61  136.93  2939.2  139.27
 2985.22  145.24 3032.25  146.87 3040.52  148.83 3135.98  152.34 3314.46  154.74
#Mann= 3 , 0 , 0
       0     .16       0 1471.69     .07       0 1511.42     .16       0
Bank Sta=1471.69,1511.42
Exp/Cntr=.3,.1

Type RM Length L Ch R = 1 ,1439.466,592.44,731.21,726.89
XS GIS Cut Line= 4
     1869028.265      315159.619     1867956.365      315779.973
     1867739.271      315934.609     1866532.721      317227.523
#Sta/Elev= 30
       0  156.68  164.14  151.82  178.77  150.38  247.96  150.51   296.2  148.18
  429.16  140.24  455.42  135.31   508.8  133.87  515.11  130.58  730.32  127.45
  745.32  125.74  841.68  123.72 1071.89  124.39 1102.28  122.89 1208.15  123.93
 1341.91  122.42 1347.27  122.11 1358.52  114.61 1368.52  114.61 1379.64  122.02
 1385.12  122.36 2259.64  122.12 2291.37  124.64 2387.79  126.93 2452.17  125.64
 2545.42  128.44 2705.97  141.89 2829.35  147.75 3072.06  153.46 3273.45  154.27
#Mann= 3 , 0 , 0
       0     .16       0 1341.91     .07       0 1385.12     .16       0
Bank Sta=1341.91,1385.12
Exp/Cntr=.3,.1

Type RM Length L Ch R = 1 ,708.260 ,808.73,679.43,539.52
XS GIS Cut Line= 4
     1868893.529      314919.438      1867580.95      315215.415
     1866969.632      315722.732     1866069.933      316020.758
#Sta/Elev= 30
       0  157.64    94.6  153.43  342.45   137.6  754.44  126.25  873.19  127.47
  894.51  126.71  901.16  125.14  930.94  124.68 1076.93  125.23 1166.46  123.42
 1302.39  124.26 1516.07  121.13 1520.63  121.02 1531.14  114.01 1541.14  114.01
 1551.83  121.14 1556.21  121.39 1628.56  122.69 1875.43  122.84 2069.42  120.58
 2205.92  122.69 2307.52  121.27  2500.8  125.23  2668.8   125.8 2673.33  127.52
 2719.72  131.23 2776.28  141.82 2809.68  145.25 2948.67  152.48 3087.72  154.57
#Mann= 3 , 0 , 0
       0     .16       0 1516.07     .07       0 1556.21     .16       0
Bank Sta=1516.07,1556.21
Exp/Cntr=.3,.1

Type RM Length L Ch R = 1 ,28.830  ,77.25,28.83,148.86
XS GIS Cut Line= 4
     1868219.849      313759.537     1867018.497      314890.205
     1866953.742      315002.054     1865996.707      315940.209
#Sta/Elev= 30
       0   157.8  195.09  156.88   274.1  152.24  343.34  145.79  413.81  135.99
  480.01  129.48   530.9  125.82  618.34  123.51  958.25  121.07 1336.92  123.08
 1413.82  121.35 1548.66  122.91 1690.58  121.73 1705.85  113.08 1715.85  113.08
 1728.07  121.22 1731.13   121.5  1926.9  121.67 2010.93  119.83 2131.43  122.93
  2282.3  121.61 2286.38  123.31 2399.99  126.07 2453.16  129.61 2537.92  130.13
  2552.9  135.99 2583.47  140.25 2737.28  147.85 2933.76  152.62 3119.16  154.29
#Mann= 3 , 0 , 0
       0     .16       0 1690.58     .07       0 1731.13     .16       0
Bank Sta=1690.58,1731.13
Exp/Cntr=.3,.1

Chan Stop Cuts=-1

--- LeithCreek.g01 (geometry) ---

Geom Title=Base Geometry Data of Leith Creek
Version=September 1998 Version 2.2

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
River Reach=Leith Creek     ,Leith Creek

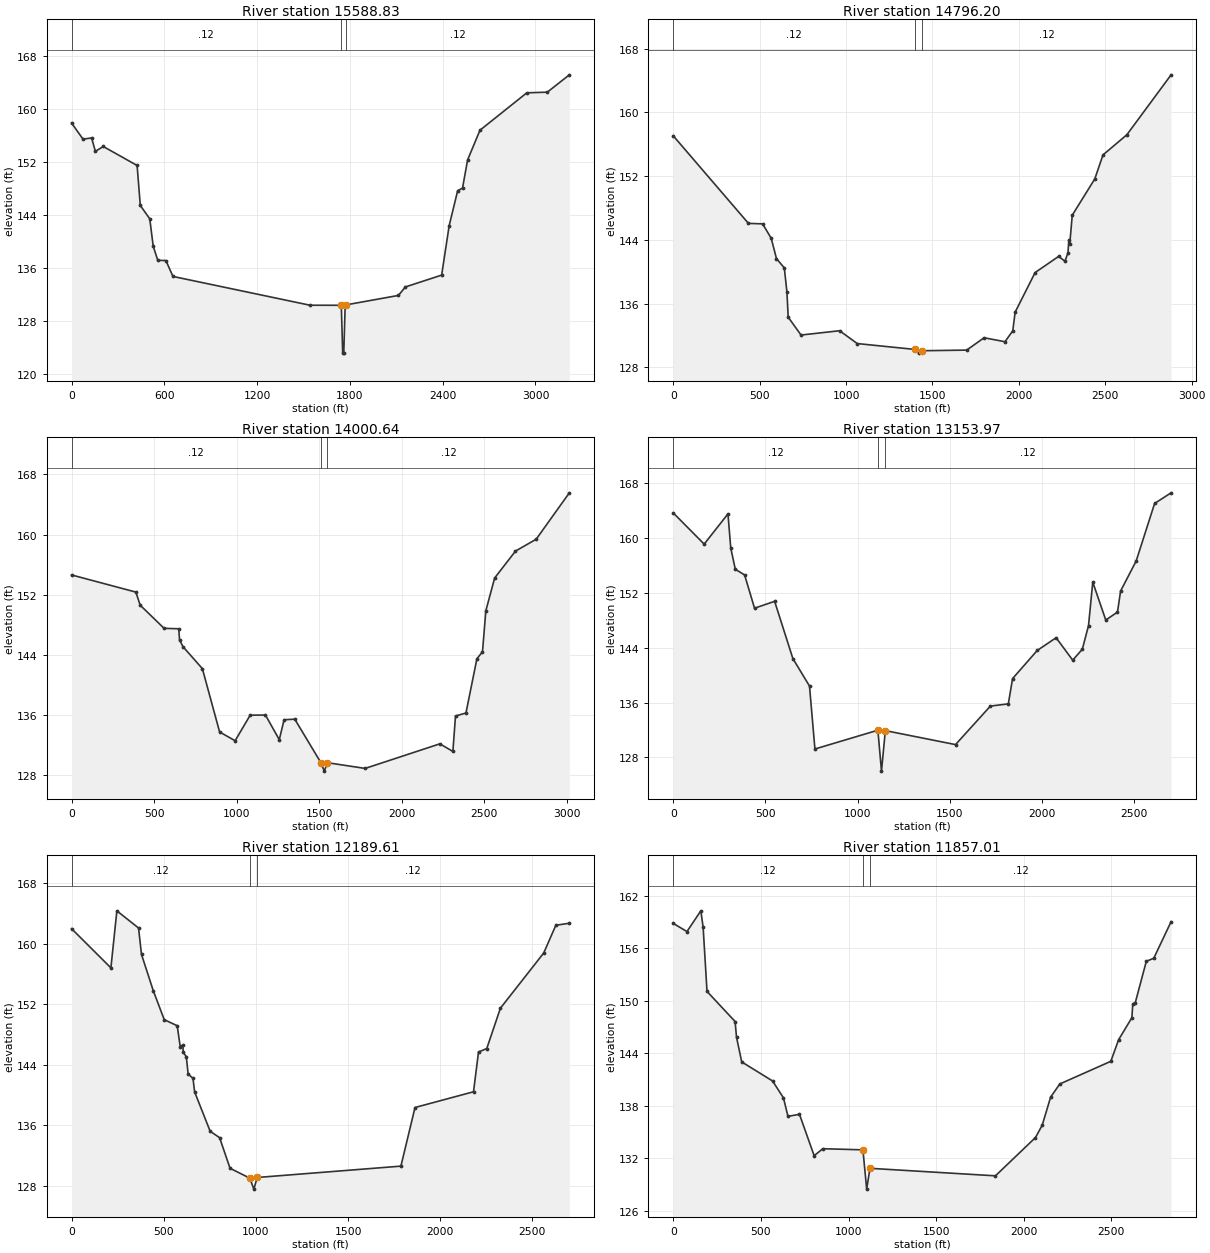
Type RM Length L Ch R = 1 ,15588.83,715,792.32,553.03
XS GIS Cut Line= 3
     1866606.414       327026.48     1864424.598      325619.601
     1863977.164      325186.005
#Sta/Elev= 30
       0   157.9   74.11  155.46   129.9  155.64  154.05  153.61  205.05  154.35
  423.99  151.48   444.5  145.44  505.73  143.42  528.03  139.29  557.46  137.15
  610.19  137.11  655.74  134.71 1541.73  130.36 1739.62  130.35 1744.46  130.29
 1753.42  123.12 1760.42  123.12 1769.43  130.33 1774.21  130.41 2113.86  131.84
 2158.59  133.12 2393.36  134.91 2442.09   142.4 2496.94  147.67 2528.28  148.05
 2561.15  152.32 2641.22  156.81 2944.03  162.46 3076.84  162.56 3219.14  165.18
#Mann= 3 , 0 , 0
       0     .12       0 1739.62      .1       0 1774.21     .12       0
Bank Sta=1739.62,1774.21
Exp/Cntr=.3,.1

Type RM Length L Ch R = 1 ,14796.20,443.47,795.56,623.82
XS GIS Cut Line= 3
     1866677.709      326111.306     1865800.847      325657.725
     1864004.959      325056.851
#Sta/Elev= 30
       0  157.05  434.85  146.07  516.97  146.01  566.62   144.2  597.13  141.65
  642.45  140.48  657.48  137.49  664.98   134.3  739.27  132.06  962.56   132.6
 1064.51  130.99 1400.24  130.25 1419.69  129.79 1440.69  130.09 1698.25  130.17
 1798.63  131.72 1919.57  131.22 1964.71  132.59 1978.37  134.93 2093.98   139.9
 2230.21  141.93 2266.59  141.32 2284.49   142.4 2288.66  143.93 2294.39  143.46
 2308.97   147.1  2439.4  151.65 2486.79  154.66 2624.96  157.19 2880.97  164.71
#Mann= 3 , 0 , 0
       0     .12       0 1400.24      .1       0 1440.69     .12       0
Bank Sta=1400.24,1440.69
Exp/Cntr=.3,.1

Type RM Length L Ch R = 1 ,14000.64,879.26,846.67,663.86
XS GIS Cut Line= 4
     1866714.322      325979.499     1865882.693      325226.776
     1865404.294      324871.835     1864144.088      324566.237
#Sta/Elev= 30
       0  154.64  389.24  152.36  415.56  150.62  560.26  147.54  649.11  147.48
  653.83     146  675.16  145.09  792.06  142.18  896.46  133.76  990.32  132.59
 1081.63  135.99 1174.01  136.01 1257.85  132.73  1286.8  135.38 1351.59  135.46
 1510.07  129.66 1530.26  128.55 1549.29  129.67 1777.69  128.91 2230.14  132.18
 2308.91  131.17 2324.82  135.88  2388.1  136.28 2454.36  143.49 2488.25  144.42
 2508.46  149.87 2561.78  154.23 2687.84  157.81 2813.37  159.39 3014.12  165.56
#Mann= 3 , 0 , 0
       0     .12       0 1510.07      .1       0 1549.29     .12       0
Bank Sta=1510.07,1549.29
Exp/Cntr=.3,.1

Type RM Length L Ch R = 1 ,13153.97,622.62,964.36,576.5
XS GIS Cut Line= 4
     1866890.065      324427.107     1865875.713      324421.187
     1865686.283      324243.802     1864275.895      324024.364
#Sta/Elev= 30
       0  163.66   167.5  159.12  296.65  163.53  311.77  158.54  336.43  155.45
  386.92  154.62  440.75  149.77  549.84  150.77   648.7  142.43  739.07  138.41
  768.49  129.23  1110.1  131.97 1129.69     126 1150.64  131.91 1531.47  129.87
 1720.65  135.49    1818  135.81 1840.97   139.5 1975.13  143.61 2077.33  145.46
  2167.3  142.19 2219.49  143.78 2253.12  147.23 2276.23  153.57 2346.74  148.04
  2410.3   149.2 2427.29  152.28 2511.84  156.66 2611.79  165.05 2701.24   166.6
#Mann= 3 , 0 , 0
       0     .12       0  1110.1      .1       0 1150.64     .12       0
Bank Sta=1110.1,1150.64
Exp/Cntr=.3,.1

Type RM Length L Ch R = 1 ,12189.61,296.83,332.6,379.04
XS GIS Cut Line= 4
     1866970.613      324280.655     1866354.222      323717.604
     1866064.187      323742.499     1864495.573      323606.975
#Sta/Elev= 30
       0  161.99  213.44  156.81   245.8  164.35  363.33  162.08  379.47  158.58
  443.33  153.79  502.77  149.96  573.16  149.16  589.56  146.37  603.99  146.64
  605.69  145.68   622.6  145.05  632.39  142.78  658.73   142.2  667.67  140.41
  751.91  135.21  803.14  134.36  859.73  130.32  966.98  129.01   988.9  127.56
 1007.12   129.1 1786.65   130.6 1863.18  138.35 2180.51  140.43 2207.63  145.68
 2252.51  146.15 2326.49  151.48 2561.47  158.78 2627.14  162.44  2700.4  162.71
#Mann= 3 , 0 , 0
       0     .12       0  966.98      .1       0 1007.12     .12       0
Bank Sta=966.98,1007.12
Exp/Cntr=.3,.1

Type RM Length L Ch R = 1 ,11857.01,287.36,583.53,338.09
XS GIS Cut Line= 4
     1867138.259      324014.685     1866405.581       323407.42
     1866088.747       323407.42     1864544.181      323110.388
#Sta/Elev= 30
       0  158.82   78.02  157.89  157.17  160.26  170.25  158.39  192.39  151.05
  352.64  147.61  360.83  145.81  390.53  142.99  566.76  140.81   628.7  138.88
  654.48  136.77  720.15     137   803.9  132.27  853.24  133.07 1082.41  132.94
 1103.71  128.45 1122.41  130.83 1838.67  129.97 2067.35  134.35  2105.8  135.76
 2153.58  138.96 2206.16  140.47  2497.4  143.06 2541.72  145.53 2617.44  148.04
 2622.58   149.6 2637.21  149.78 2699.82  154.49 2742.41  154.84 2841.32  159.02
#Mann= 3 , 0 , 0
       0     .12       0 1082.41      .1       0 1122.41     .12       0
Bank Sta=1082.41,1122.41
Exp/Cntr=.3,.1