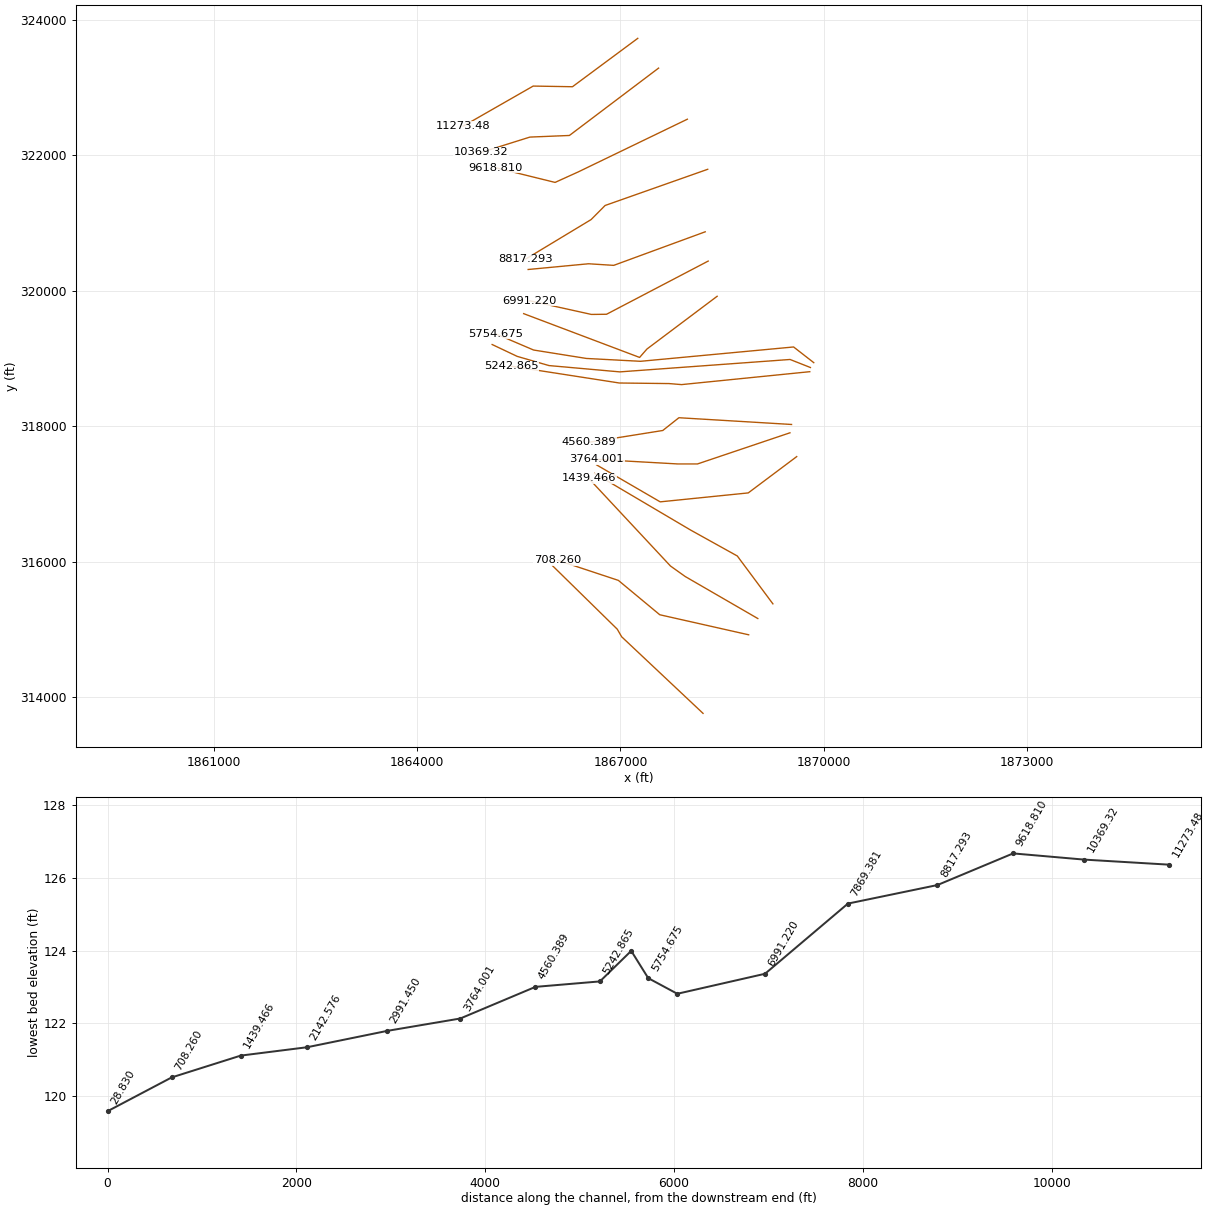
HEC-RAS study LeithCreek.prj: Leith Creek Approximate Study

--- LeithCreek.g01 (geometry) --- (continued)

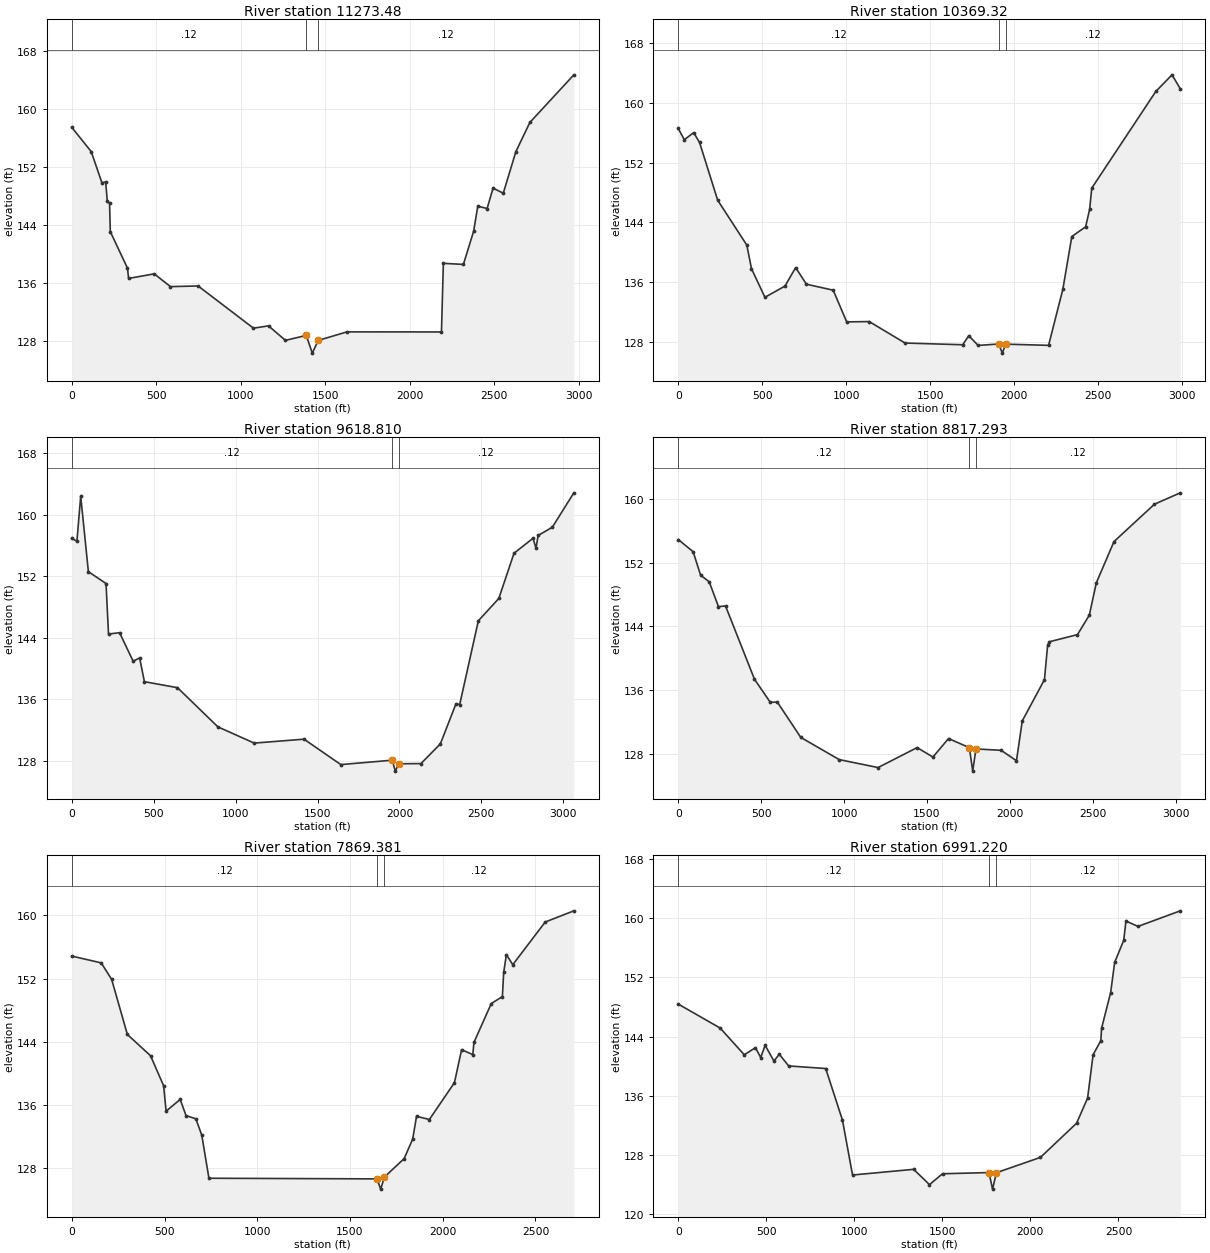
Type RM Length L Ch R = 1 ,11273.48,631.55,904.16,759.35
XS GIS Cut Line= 4
     1867256.195      323724.137     1866292.219      323009.728
     1865712.274      323019.468     1864678.638      322428.036
#Sta/Elev= 30
       0  157.49  115.19  154.14  178.42  149.84  200.75  149.97  210.11  147.29
  223.66  147.02  227.95  143.11  329.52  138.08  336.32  136.66  488.05  137.29
  583.98  135.53  747.44  135.62 1075.11   129.8 1164.05  130.12 1264.15  128.12
 1387.32   128.8 1423.21  126.36 1458.39  128.11 1627.99  129.29 2187.48  129.28
 2198.68  138.74 2317.21  138.59 2377.92  143.17 2402.42  146.62 2457.61   146.3
  2492.8  149.11 2553.12  148.41 2627.91  154.15 2710.42  158.16 2970.75  164.73
#Mann= 3 , 0 , 0
       0     .12       0 1387.32      .1       0 1458.39     .12       0
Bank Sta=1387.32,1458.39
Exp/Cntr=.3,.1

Type RM Length L Ch R = 1 ,10369.32,683.71,750.51,603.24
XS GIS Cut Line= 4
     1867563.744      323284.781     1866247.279      322290.331
      1865664.33      322266.496     1864942.252      322039.938
#Sta/Elev= 30
       0  156.56   36.03  155.05    91.9     156  126.82  154.69  234.89  146.96
   408.6  140.94  436.13   137.8   516.3  133.97  635.63  135.47   699.2  137.94
  763.41  135.72  922.82  134.92 1003.33  130.68  1137.4  130.72 1350.78  127.85
 1694.26  127.62 1730.18  128.83 1786.05  127.53 1907.67  127.72 1930.35   126.5
 1949.53   127.7 2205.53  127.54 2290.45  135.03 2343.95   142.1 2426.32   143.4
 2450.15  145.75 2462.82  148.58 2844.34  161.51 2940.66  163.73 2990.07  161.86
#Mann= 3 , 0 , 0
       0     .12       0 1907.67      .1       0 1949.53     .12       0
Bank Sta=1907.67,1949.53
Exp/Cntr=.3,.1

Type RM Length L Ch R = 1 ,9618.810,674.26,801.52,970.82
XS GIS Cut Line= 4
     1867988.455      322530.553     1866376.669      321751.916
     1866035.761      321597.327      1865161.93      321812.937
#Sta/Elev= 30
       0  156.89   31.36  156.54   54.55  162.38  101.39  152.58  209.15  151.04
  224.25  144.48  291.71  144.65  374.58  140.95  414.31  141.37  443.29  138.29
  645.05  137.51  891.92  132.42 1113.47  130.31 1417.52  130.82 1642.12  127.52
 1955.32  128.09 1974.97  126.67 1994.84  127.62 2131.03  127.65 2249.66  130.21
 2345.05  135.42 2367.74  135.32 2481.51   146.2 2606.43   149.1 2699.17  154.97
 2815.28  156.92 2833.33  155.62 2846.38  157.28 2932.98  158.35 3064.37  162.82
#Mann= 3 , 0 , 0
       0     .12       0 1955.32      .1       0 1994.84     .12       0
Bank Sta=1955.32,1994.84
Exp/Cntr=.3,.1

Type RM Length L Ch R = 1 ,8817.293,888.25,947.91,433.76
XS GIS Cut Line= 4
     1868288.682       321790.97     1866774.554      321256.994
     1866567.559      321048.802     1865601.286      320465.578
#Sta/Elev= 30
       0  154.93   89.95  153.39  134.88  150.44  186.59  149.62  242.65  146.49
   285.2  146.57  459.71  137.36  555.22  134.45  597.25  134.49  739.05  130.04
  970.71  127.25 1205.03  126.25 1440.61  128.76 1535.93  127.57 1630.02   129.9
 1755.67  128.75 1775.88   125.8 1795.22  128.59  1947.1  128.42 2039.71  127.11
 2074.69  132.12  2208.4   137.3 2227.68  141.65 2238.27  142.07 2407.73  142.97
 2479.11  145.42  2521.3  149.48 2627.83  154.67 2871.84  159.37 3027.75   160.8
#Mann= 3 , 0 , 0
       0     .12       0 1755.67      .1       0 1795.22     .12       0
Bank Sta=1755.67,1795.22
Exp/Cntr=.3,.1

Type RM Length L Ch R = 1 ,7869.381,551.13,878.16,669.55
XS GIS Cut Line= 4
     1868252.069      320868.321     1866901.048      320372.825
     1866529.223       320396.42     1865637.899      320311.804
#Sta/Elev= 30
       0  154.85  158.51  153.99  214.76  151.91  299.68  144.91  424.56  142.21
  495.34   138.4  508.56  135.18  584.65  136.67  615.93  134.62  668.87  134.21
  700.82  132.15   739.5  126.67 1645.72  126.59 1665.53  125.29 1685.76  126.83
 1791.98  129.16 1838.04  131.64  1858.8  134.53 1927.91  134.12 2063.12  138.79
 2101.81  142.98 2162.17  142.35 2168.11  143.89 2261.83  148.83 2321.65  149.71
 2328.73  152.79  2343.3  155.03 2377.67  153.76 2552.55  159.17 2706.92  160.59
#Mann= 3 , 0 , 0
       0     .12       0 1645.72      .1       0 1685.76     .12       0
Bank Sta=1645.72,1685.76
Exp/Cntr=.3,.1

Type RM Length L Ch R = 1 ,6991.220,682.73,928.65,377.57
XS GIS Cut Line= 4
     1868296.005      320436.288     1866794.973      319650.956
     1866571.429      319648.543     1865659.867      319850.479
#Sta/Elev= 30
       0   148.4  237.93  145.16  375.08  141.54   438.4   142.5  468.45  141.17
  493.47  142.82  543.55  140.69  573.89  141.62  627.04  140.03  837.47  139.68
  932.82  132.68  989.88  125.27 1336.85  126.04 1426.78  123.97 1500.76  125.44
 1764.85   125.6 1784.98  123.36 1806.79  125.58 2057.28  127.66 2262.23  132.28
 2324.76  135.68 2355.92  141.54 2400.05  143.46 2404.05  145.12 2455.64  149.95
 2478.52  154.05 2529.84  157.02 2542.61  159.64 2610.86  158.91 2851.28  161.02
#Mann= 3 , 0 , 0
       0     .12       0 1764.85      .1       0 1806.79     .12       0
Bank Sta=1764.85,1806.79
Exp/Cntr=.3,.1

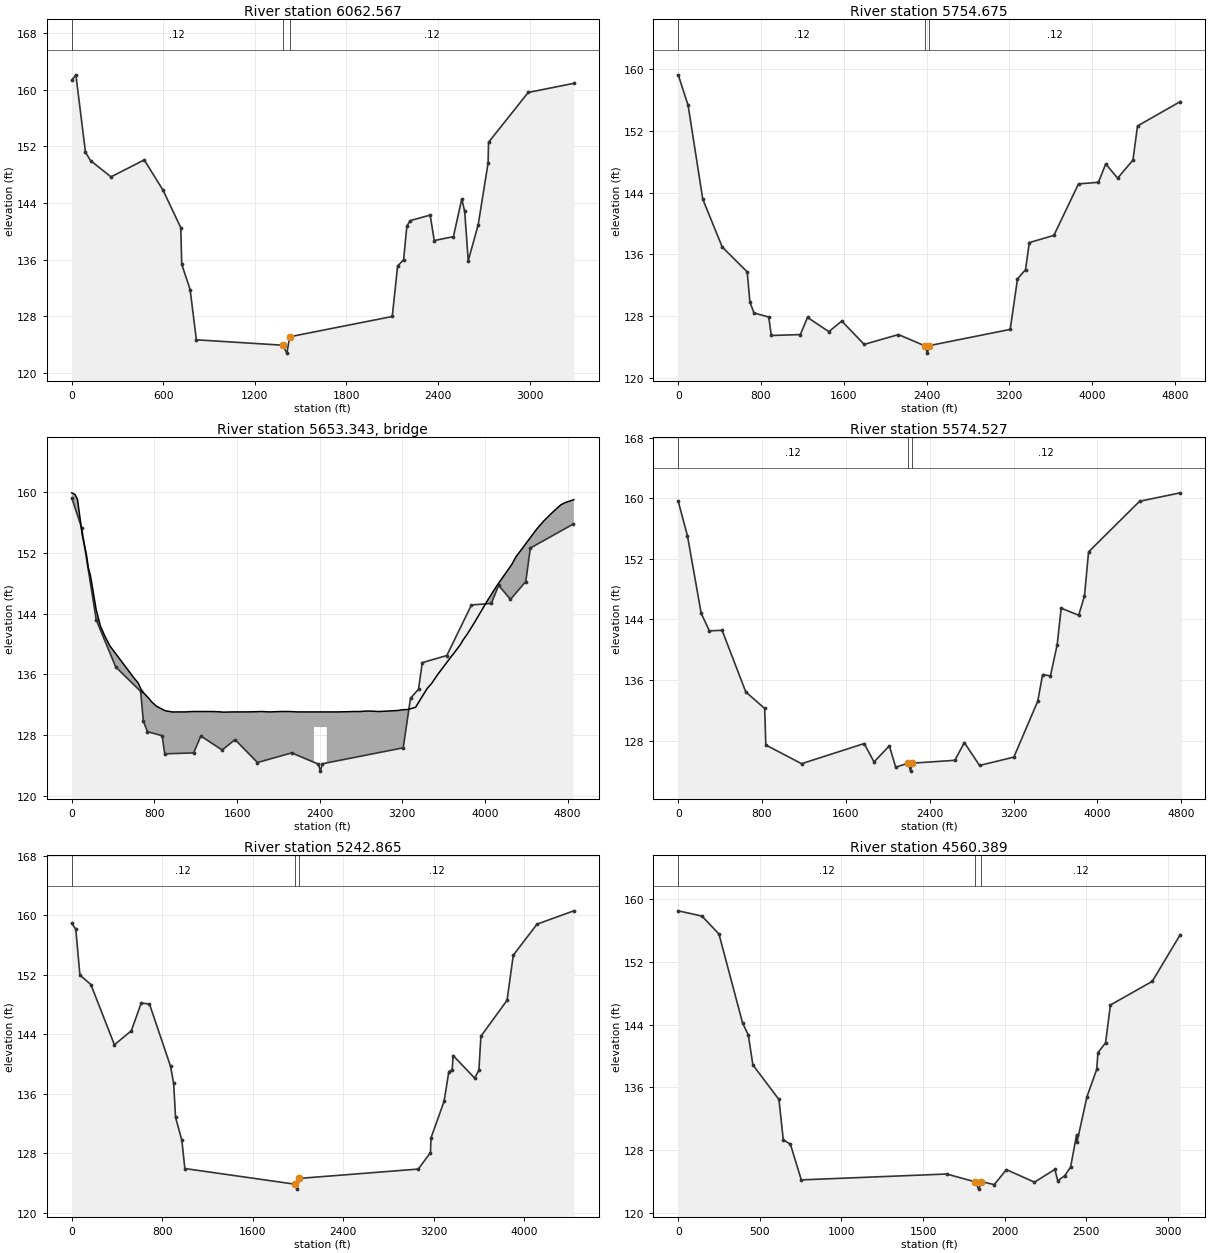
Type RM Length L Ch R = 1 ,6062.567,396.74,307.89,441.67
XS GIS Cut Line= 4
     1868427.811      319916.383     1867391.878      319137.937
      1867283.14      319013.884     1865571.996      319660.092
#Sta/Elev= 30
       0  161.34   26.97  162.09   89.77  151.17  123.08  149.98  256.97  147.69
   474.9  150.08  598.38  145.79  714.25  140.52  720.46  135.36  775.55  131.77
  816.41  124.69  1381.9  123.93 1409.49  122.81 1427.81  125.12 2100.01  127.98
 2135.14  135.12 2174.37  135.97  2195.6  140.74  2217.8  141.52 2348.43  142.29
 2375.29   138.7 2500.72  139.25 2555.55  144.58 2574.76   142.8 2597.93  135.85
 2663.25  140.94 2728.03  149.66 2730.94  152.57 2990.79   159.6 3289.88  160.89
#Mann= 3 , 0 , 0
       0     .12       0  1381.9      .1       0 1427.81     .12       0
Bank Sta=1381.9,1427.81
Exp/Cntr=.3,.1

Type RM Length L Ch R = 1 ,5754.675,164.4,180.15,276.86
XS GIS Cut Line= 6
     1869854.255      318936.705     1869556.526      319168.271
     1867296.514      318956.638     1866497.618      318998.802
     1865718.694      319123.075     1865157.247      319362.743
#Sta/Elev= 30
       0  159.23   95.35  155.29  237.14  143.15  425.27  136.96  666.52  133.75
  692.71  129.84  732.25  128.43  874.59  127.91  899.62  125.52 1180.06  125.64
 1249.36  127.86 1455.68  126.02 1580.64  127.39 1797.02  124.37  2128.4  125.64
 2387.33  124.16 2407.06  123.24    2426  124.21 3208.58  126.31 3278.92  132.84
 3356.37  134.03 3392.91  137.53 3630.59  138.47 3868.78  145.13 4061.23  145.33
 4131.92  147.71 4246.63  145.86 4394.76  148.21 4438.93  152.62 4852.52  155.77
#Mann= 3 , 0 , 0
       0     .12       0 2387.33      .1       0    2426     .12       0
Bank Sta=2387.33,2426
Exp/Cntr=.3,.1

Type RM Length L Ch R = 3 ,5653.343,,,
BEGIN DESCRIPTION:
NC 83 Across Leith Creek - Data Available from NCDOT Bridge Inspection Reports
END DESCRIPTION:
Bridge Culvert--1,0,-1,-1, 0
Deck Dist Width WeirC Skew NumUp NumDn MinLoCord MaxHiCord MaxSubmerge Is_Ogee
81.33,40,2.6,,74,74,,,.95,0,2,2,,
       0   31.23   55.17   91.01  102.39  142.55  160.31  182.03  236.42  277.31
  318.54  370.14  554.25  598.57  642.78  676.91  744.35     773  819.11  902.89
  974.24 1029.58 1100.02  1166.1 1251.42 1365.19 1432.19 1467.18  1552.9 1672.35
 1773.13 1837.32 1916.95 2025.03 2098.98 2189.99    2345 2363.27    2468 2480.09
  2571.1 2741.75 2792.95 2844.14 2889.65 2974.97 3054.61 3159.83 3203.28  3253.7
 3327.65 3412.45 3441.41 3481.23  3543.8  3669.2 3703.07 3761.08  3788.4 3828.21
 3890.78 4026.64 4112.63  4260.2 4300.34 4340.16 4408.42 4501.13 4567.69 4617.85
 4662.37 4732.65 4775.61    4860
   159.9  159.69  159.05  155.47  154.27  151.72  150.03  148.93  144.49  142.36
  141.07  139.71  136.38  135.58  134.85  133.82  132.85  132.37   131.8   131.2
  131.03  131.04  131.04  131.09  131.09  131.09  131.05  131.01  131.04  131.04
  131.06  131.09  131.04  131.09  131.09  131.04  131.04  131.04  131.04  131.04
  131.04  131.09  131.09  131.15  131.15  131.09  131.15  131.23  131.33  131.36
  131.64  133.52  134.15  134.75     136  138.26  138.84  139.89  140.53  141.29
  142.65  145.77  147.62  150.49  151.49   152.2  153.45  155.13  156.18  156.86
  157.44  158.31  158.61     159
                                                                                
                                                                                
                                                                                
                                                  129.04  129.04  129.04
                                                                                
                                                                                
                                                                                
                                
       0   31.23   55.17   91.01  102.39  142.55  160.31  182.03  236.42  277.31
  318.54  370.14  554.25  598.57  642.78  676.91  744.35     773  819.11  902.89
  974.24 1029.58 1100.02  1166.1 1251.42 1365.19 1432.19 1467.18  1552.9 1672.35
 1773.13 1837.32 1916.95 2025.03 2098.98    2155 2189.99    2278 2363.27 2480.09
  2571.1 2741.75 2792.95 2844.14 2889.65 2974.97 3054.61 3159.83 3203.28  3253.7
 3327.65 3412.45 3441.41 3481.23  3543.8  3669.2 3703.07 3761.08  3788.4 3828.21
 3890.78 4026.64 4112.63  4260.2 4300.34 4340.16 4408.42 4501.13 4567.69 4617.85
 4662.37 4732.65 4775.61 4817.26
   159.9  159.69  159.05  155.47  154.27  151.72  150.03  148.93  144.49  142.36
  141.07  139.71  136.38  135.58  134.85  133.82  132.85  132.37   131.8   131.2
  131.03  131.04  131.04  131.09  131.09  131.09  131.05  131.01  131.04  131.04
  131.06  131.09  131.04  131.09  131.09  131.04  131.04  131.04  131.04  131.04
  131.04  131.09  131.09  131.15  131.15  131.09  131.15  131.23  131.33  131.36
  131.64  133.52  134.15  134.75     136  138.26  138.84  139.89  140.53  141.29
  142.65  145.77  147.62  150.49  151.49   152.2  153.45  155.13  156.18  156.86
  157.44  158.31  158.61     159
                                                                                
                                                                                
                                                                                
                                          129.04  129.04  129.04
                                                                                
                                                                                
                                                                                
                                
BR Coef=-1 , 1 , 0 ,, 0 ,,,.8,0,1.2,0,
WSPro=,,,, 1 ,,,, 0 ,,,, 0 ,,,,-1 ,-1 ,-1 , 0 , 0 , 0 , 0 , 0
BC Design=,, 0 ,, 0 ,,,,,,

Type RM Length L Ch R = 1 ,5574.527,280.89,331.66,243.62
XS GIS Cut Line= 6
     1869804.633      318865.029     1869504.148      318983.569
     1866990.847      318800.496     1865945.624        318893.7
     1865477.382      319029.069     1865106.783      319204.382
#Sta/Elev= 30
       0  159.59   88.24  155.02   218.9  144.82  297.01   142.5   418.7  142.57
  644.64  134.44  824.94  132.26  835.96  127.44 1177.16  124.97 1774.68  127.63
 1868.68   125.2 2014.96  127.33  2075.7   124.5 2194.69  125.05 2217.13  123.99
 2233.03  125.04 2640.14  125.42 2730.54  127.76 2875.93  124.74 3203.42  125.84
 3431.35  133.23 3477.97  136.73 3552.67  136.56 3616.88  140.69 3655.07  145.49
 3822.32  144.56 3877.13  147.09 3916.33  152.92  4403.6   159.6 4791.91  160.71
#Mann= 3 , 0 , 0
       0     .12       0 2194.69      .1       0 2233.03     .12       0
Bank Sta=2194.69,2233.03
Exp/Cntr=.3,.1

Type RM Length L Ch R = 1 ,5242.865,656.69,682.48,813.77
XS GIS Cut Line= 5
     1869795.674      318803.347     1867901.876      318612.624
     1867718.093       318627.94     1866984.262      318636.259
     1865388.931      318883.896
#Sta/Elev= 30
       0  158.89   35.54  158.14   71.75  151.96  169.04  150.67  376.75  142.57
  526.37  144.46   613.5  148.18  686.37  148.06  872.54  139.68  900.25  137.37
  917.03  132.79  972.55  129.73  999.09  125.92 1969.65  123.82 1992.04  123.15
 2009.56  124.59 3061.77  125.85 3169.44  128.07 3173.66  130.03 3289.67  134.97
  3331.6  138.96  3361.2  139.18 3369.67  141.12 3559.54  138.09 3597.08  139.14
 3615.03  143.72 3845.87  148.55 3901.03  154.62 4111.01   158.8 4436.11  160.59
#Mann= 3 , 0 , 0
       0     .12       0 1969.65      .1       0 2009.56     .12       0
Bank Sta=1969.65,2009.56
Exp/Cntr=.3,.1

Type RM Length L Ch R = 1 ,4560.389,516.38,796.39,455.68
XS GIS Cut Line= 4
     1869526.202      318024.222     1867863.564      318123.781
      1867625.22      317935.212     1866532.721      317760.608
#Sta/Elev= 30
       0  158.55  145.46  157.88  249.59  155.58  394.53   144.2  429.27   142.7
  457.16  138.87  616.97  134.45  643.62  129.29  687.07  128.75  753.83  124.18
 1644.76  124.93 1820.93  123.92 1840.53     123 1857.84  123.95 1936.08  123.58
 2010.54  125.49 2182.36  123.89  2307.4  125.52 2325.05  124.07 2367.24   124.7
  2403.8  125.82 2440.64  129.97 2443.53  129.06 2503.96   134.8 2564.06  138.32
 2571.22  140.44 2617.94  141.69 2647.64  146.52 2903.96  149.54  3075.9  155.52
#Mann= 3 , 0 , 0
       0     .12       0 1820.93      .1       0 1857.84     .12       0
Bank Sta=1820.93,1857.84
Exp/Cntr=.3,.1

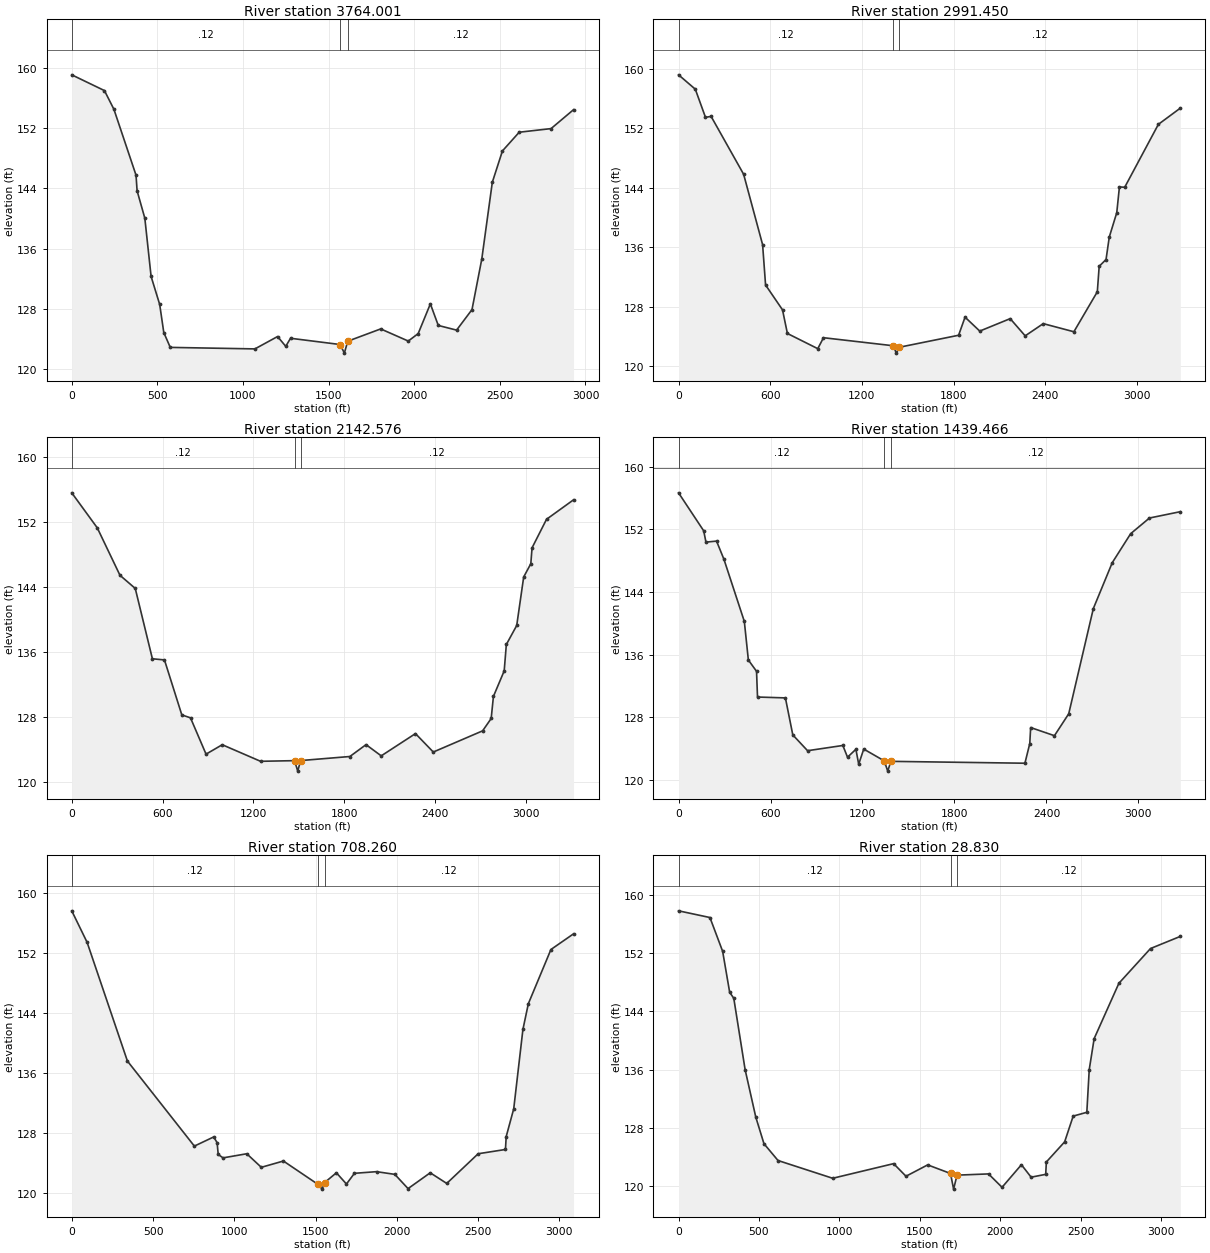
Type RM Length L Ch R = 1 ,3764.001,641.77,772.55,590.33
XS GIS Cut Line= 4
      1869502.77      317901.202     1868137.431      317441.249
     1867849.326      317441.343     1866649.883      317508.711
#Sta/Elev= 30
       0  159.03  190.83  156.94   246.2  154.46  375.39  145.72  381.49  143.66
  426.68  140.02  463.31   132.3  513.54  128.58  537.43  124.86   575.3  122.89
 1069.62  122.69 1201.87  124.33 1249.69  123.03 1277.55   124.1 1567.64  123.27
 1591.87  122.13 1611.67  123.71  1804.1  125.34 1965.11  123.73    2023  124.72
 2094.09  128.66 2140.37   125.8 2247.32  125.18 2337.22   127.9 2394.37   134.6
 2455.97  144.79 2515.02  148.94 2612.92  151.42 2798.97   151.9 2930.17  154.41
#Mann= 3 , 0 , 0
       0     .12       0 1567.64      .1       0 1611.67     .12       0
Bank Sta=1567.64,1611.67
Exp/Cntr=.3,.1

Type RM Length L Ch R = 1 ,2991.450,942.57,848.87,152.69
XS GIS Cut Line= 4
     1869602.357      317549.717     1868887.353      317013.907
     1867587.176      316881.896     1866649.883      317426.698
#Sta/Elev= 30
       0  159.16   109.7  157.23  176.31  153.45     213  153.58  425.95  145.81
  550.25  136.35  569.61  130.94  680.58   127.6  712.48  124.43  911.28  122.39
  948.79  123.86 1405.76  122.78 1425.25  121.79 1445.17  122.58 1833.13  124.19
 1875.36  126.62  1971.6  124.75 2170.82  126.42 2268.98  124.11 2387.25  125.75
  2587.8  124.66 2741.19  130.03 2753.29  133.45 2798.26  134.36 2819.35  137.37
 2868.42  140.65 2885.83  144.11  2920.4  144.06  3140.8  152.51 3284.48  154.69
#Mann= 3 , 0 , 0
       0     .12       0 1405.76      .1       0 1445.17     .12       0
Bank Sta=1405.76,1445.17
Exp/Cntr=.3,.1

Type RM Length L Ch R = 1 ,2142.576,651.99,703.11,464.73
XS GIS Cut Line= 4
     1869250.872      315376.368     1868725.566      316082.797
     1868031.217      316468.546     1866619.128      317302.213
#Sta/Elev= 30
       0   155.6  168.49  151.29  318.46  145.45  419.46  143.83  532.65  135.17
  612.35  135.03  727.05  128.26  784.36   127.9  887.04  123.43  994.09  124.59
 1247.16  122.55 1471.69  122.63 1492.82  121.34 1511.42  122.64  1837.1  123.14
 1943.87   124.6 2044.17  123.22 2270.35  125.96 2388.08  123.69 2713.99   126.3
 2770.52  127.82 2785.35  130.54 2856.47  133.68 2870.61  136.93  2939.2  139.27
 2985.22  145.24 3032.25  146.87 3040.52  148.83 3135.98  152.34 3314.46  154.74
#Mann= 3 , 0 , 0
       0     .12       0 1471.69      .1       0 1511.42     .12       0
Bank Sta=1471.69,1511.42
Exp/Cntr=.3,.1

Type RM Length L Ch R = 1 ,1439.466,592.44,731.21,726.89
XS GIS Cut Line= 4
     1869028.265      315159.619     1867956.365      315779.973
     1867739.271      315934.609     1866532.721      317227.523
#Sta/Elev= 30
       0  156.68  164.14  151.82  178.77  150.38  247.96  150.51   296.2  148.18
  429.16  140.24  455.42  135.31   508.8  133.87  515.11  130.58  697.08  130.47
  745.32  125.74  841.68  123.72 1071.89  124.39 1102.28  122.89 1157.04   123.9
 1175.22  121.99 1208.15  123.93 1341.91  122.42 1364.71  121.11 1385.12  122.36
 2259.64  122.12 2291.37  124.64 2297.06  126.68 2452.17  125.64 2545.42  128.44
 2705.97  141.89 2829.35  147.75 2949.57  151.46 3072.06  153.46 3273.45  154.27
#Mann= 3 , 0 , 0
       0     .12       0 1341.91      .1       0 1385.12     .12       0
Bank Sta=1341.91,1385.12
Exp/Cntr=.3,.1

Type RM Length L Ch R = 1 ,708.260 ,808.73,679.43,539.52
XS GIS Cut Line= 4
     1868893.529      314919.438      1867580.95      315215.415
     1866969.632      315722.732     1866069.933      316020.758
#Sta/Elev= 30
       0  157.64    94.6  153.43  342.45   137.6  754.44  126.25  873.19  127.47
  894.51  126.71  901.16  125.14  930.94  124.68 1076.93  125.23 1166.46  123.42
 1302.39  124.26 1516.07  121.13 1541.07  120.51 1556.21  121.39 1628.56  122.69
 1690.33  121.19 1739.51  122.62 1875.43  122.84 1988.02  122.48 2069.42  120.58
 2205.92  122.69 2307.52  121.27  2500.8  125.23  2668.8   125.8 2673.33  127.52
 2719.72  131.23 2776.28  141.82 2809.68  145.25 2948.67  152.48 3087.72  154.57
#Mann= 3 , 0 , 0
       0     .12       0 1516.07      .1       0 1556.21     .12       0
Bank Sta=1516.07,1556.21
Exp/Cntr=.3,.1

Type RM Length L Ch R = 1 ,28.830  ,77.25,28.83,148.86
XS GIS Cut Line= 4
     1868219.849      313759.537     1867018.497      314890.205
     1866953.742      315002.054     1865996.707      315940.209
#Sta/Elev= 30
       0   157.8  195.09  156.88   274.1  152.24  317.78  146.61  343.34  145.79
  413.81  135.99  480.01  129.48   530.9  125.82  618.34  123.51  958.25  121.07
 1336.92  123.08 1413.82  121.35 1548.66  122.91 1690.58  121.73 1709.78  119.58
 1731.13   121.5  1926.9  121.67 2010.93  119.83 2131.43  122.93 2191.66  121.22
  2282.3  121.61 2286.38  123.31 2399.99  126.07 2453.16  129.61 2537.92  130.13
  2552.9  135.99 2583.47  140.25 2737.28  147.85 2933.76  152.62 3119.16  154.29
#Mann= 3 , 0 , 0
       0     .12       0 1690.58      .1       0 1731.13     .12       0
Bank Sta=1690.58,1731.13
Exp/Cntr=.3,.1